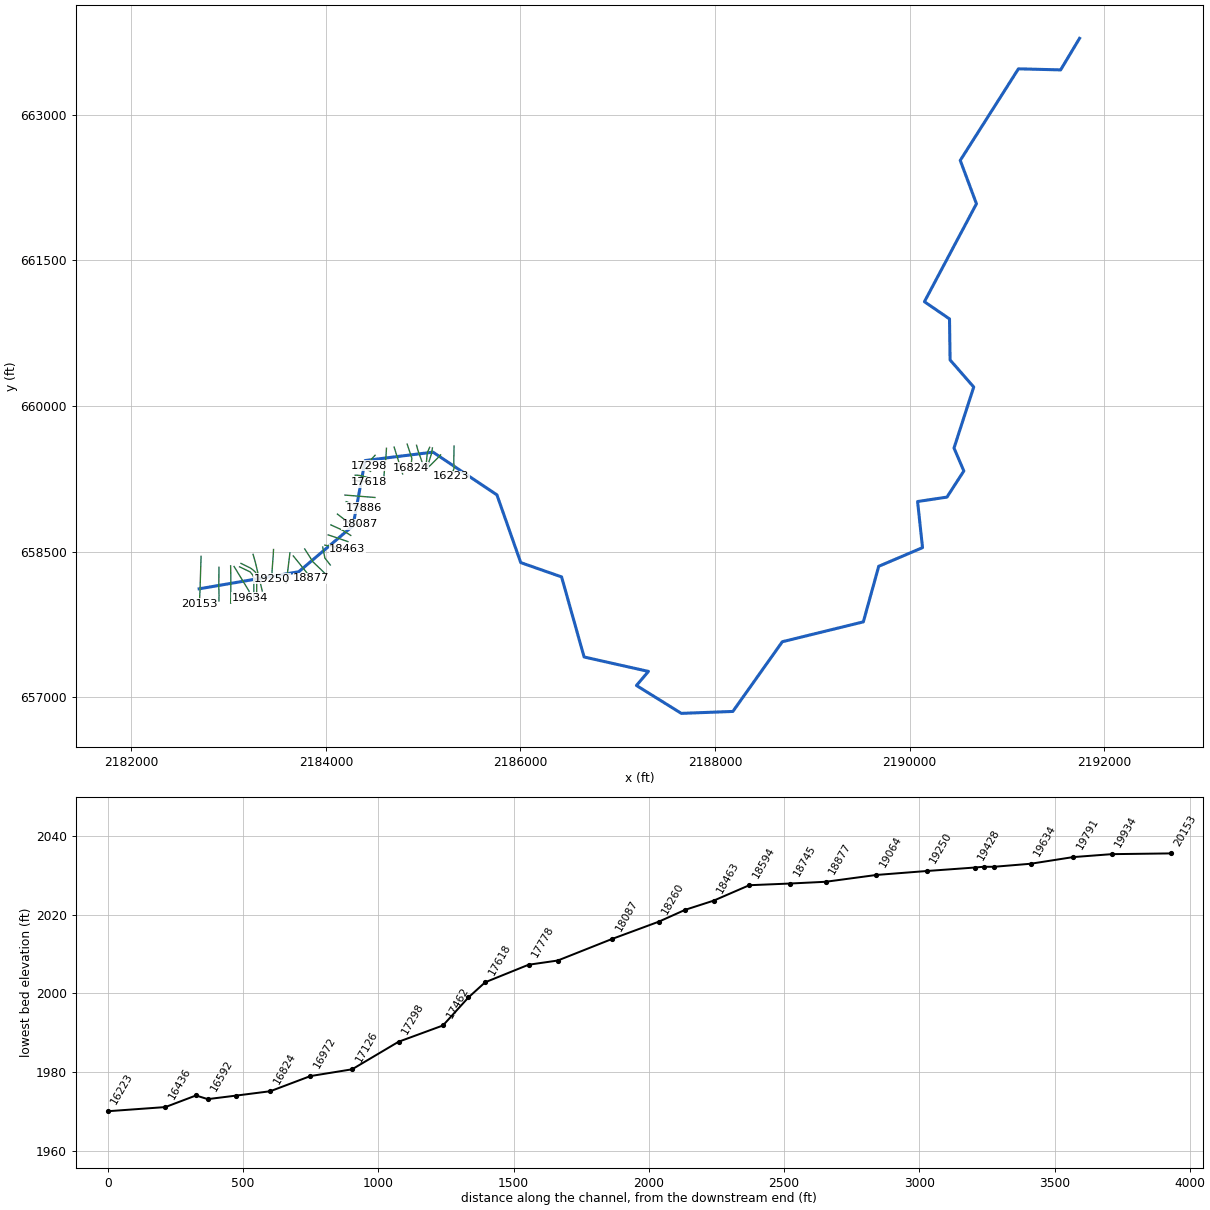
--- BIGRN.prj (project) ---

Proj Title=BIGRN
Current Plan=p01
Default Exp/Contr=0,0
English Units
Geom File=g01
Flow File=f01
Plan File=p01
BEGIN DESCRIPTION:
--------- MODELED AS PART OF WVEMD CTP PROGRAM, 2023----------
Stream Name: Big Run
Flood Zone:  AFH
Upshur County, WV
HEC-RAS Version: RAS 6.3
Vertical Datum: NAVD88
Projection: NAD 1983 StatePlane West Virginia S FIPS 4702 (US Feet)
Terrain: 1-meter LIDAR (FEMA Region III 3DEP collected 2016-2018)
Land Use: 2019 NLCD
Hydrologic Method:
WV SIR2010-5033 regression equations
Additional Model Notes:
None
END DESCRIPTION:
DSS Export Rating Curves= 0
DSS Export Rating Curve Sorted= 0
DSS Export Volume Flow Curves= 0
DXF OffsetX= 0
DXF OffsetY= 0
DXF ScaleX= 0
DXF ScaleY= 0

--- BIGRN.p01 (plan) ---

Plan Title=Floodplain
Program Version=4.00
Geom File=g01
Flow File=f01
K Sum by GR=0
Std Step Tol=0.01
Critical Tol=0.01
Num of Std Step Trials=20
Max Error Tol=0.3
Flow Tol Ratio=0.001
Split Flow NTrial=30
Split Flow Tol=0.02
Split Flow Ratio=0.02
Log Output Level=0
Friction Slope Method=1
Unsteady Friction Slope Method=2
Unsteady Bridges Friction Slope Method=1
Global Log Level=0
CheckData=False
Run HTab=0
Run UNet=0
Run PostProcess=0
UNET Theta=0
UNET Theta Warmup=0
UNET ZTol=0
UNET ZSATol=0
UNET MxIter=0
UNET MaxInSteps=0
UNET DtIC=0
UNET DtMin=0
UNET MaxCRTS=0
UNET WFStab=0
UNET SFStab=0
UNET WFX=0
UNET SFX=0
UNET DSS MLevel=0
UNET DZMax Abort=0
UNET Convert EG Bridges=0
UNET Use Existing IB Tables=0
UNET Froude Limit=0
UNET Froude Power=0
Write IC File=0
Echo Input=False
Echo Output=False
Write Detailed=0

--- BIGRN.f01 (steady flow) ---

Flow Title=Flows
Program Version=6.30
Number of Profiles= 1
Profile Names=01pct
River Rch & RM=BIGRN,Main,20153
     367
River Rch & RM=BIGRN,Main,15891
     428
River Rch & RM=BIGRN,Main,13180
     552
River Rch & RM=BIGRN,Main,11300
     628
River Rch & RM=BIGRN,Main,8831
     698
River Rch & RM=BIGRN,Main,3988
     819
Boundary for River Rch & Prof#=BIGRN,Main            , 1
Up Type= 0
Dn Type= 3
Dn Slope=0.00564
DSS Import GetInterval= 0
DSS Import GetPeak= 0
DSS Import FillOption= 0

--- BIGRN.g01 (geometry) ---

Geom Title=Geometry
Program Version=6.30

River Reach=BIGRN           ,Main
Reach XY= 30
     2182697.896      658118.766      2183721.59      658294.585
     2184279.609      658768.244     2184403.747      659439.584
     2185101.501      659526.321     2185758.676      659086.201
      2186003.46      658388.791      2186423.32      658241.416
     2186654.741      657416.778      2187315.98       657268.23
     2187192.758      657123.431     2187653.825       656836.18
     2188183.714      656856.097     2188691.913      657573.825
     2189524.736      657778.546     2189682.784      658350.559
     2190133.006      658542.976     2190082.383      659017.664
     2190384.286      659063.222     2190557.616      659332.473
     2190456.628      659568.072      2190659.29      660196.831
     2190416.279      660475.812     2190410.413      660898.219
     2190152.522      661075.269      2190687.42      662083.796
     2190520.729      662530.383     2191118.668      663473.465
     2191552.722      663462.448     2191747.056      663787.473

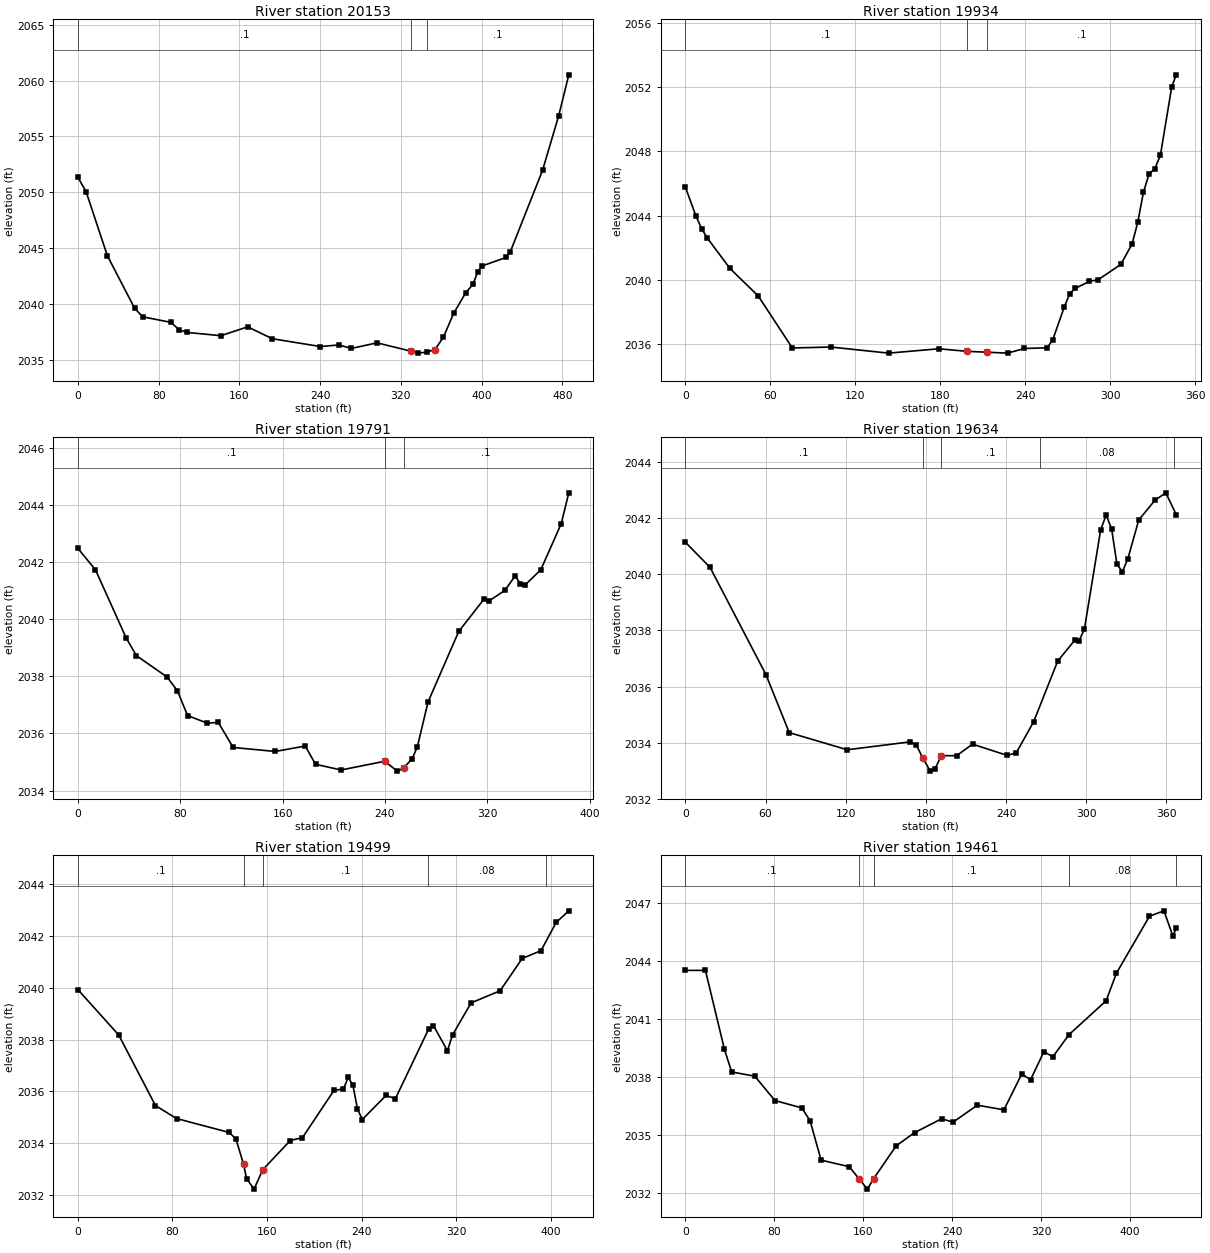
Type RM Length L Ch R = 1 ,20153   ,218.8,218.8,218.8
XS GIS Cut Line= 3
2182718.08710234658453.286290841     2182707.298      658116.202
 2182701.3193086657967.141869842
#Sta/Elev= 30
       0 2051.34     8.1 2050.05    29.1 2044.34    56.1 2039.64    64.1 2038.87
    92.2 2038.37   100.2 2037.71   108.2 2037.47   141.6 2037.18   168.2 2037.97
   192.5 2036.91   240.2 2036.21   258.6 2036.35     271 2036.04   296.3 2036.54
   330.42035.787   337.2 2035.62   345.92035.722   353.8 2035.94   362.2 2037.05
   372.3 2039.18   384.3 2041.02   391.4 2041.77   396.3 2042.91   400.3 2043.41
   424.3 2044.18   428.4 2044.67   460.4 2051.97   476.4 2056.85   486.4 2060.51
#Mann= 3 ,-1,0
       0      .1       0   330.4    .045       0   345.9      .1       0
Bank Sta=330.4,353.8
XS Rating Curve= 0 ,0
Exp/Cntr=0.3,0.1

Type RM Length L Ch R = 1 ,19934   ,140.8,142.8,140.5
XS GIS Cut Line= 4
2182901.45490184 658340.646071152182900.58172184 658132.82923172
2182902.32808184658053.3698519382182901.45490184657993.993612101
#Sta/Elev= 30
       0 2045.76     7.5 2043.95    11.5 2043.17    15.5 2042.59    31.5  2040.7
    51.5 2038.98    75.5 2035.75   102.6 2035.81   143.5 2035.43   178.9  2035.7
   198.82035.543   213.32035.486   227.5 2035.43   239.5 2035.72   255.5 2035.76
   259.5 2036.27   267.5 2038.28   271.5 2039.14   275.5 2039.47   285.4  2039.9
   291.5    2040   307.5 2040.95   315.5 2042.23   319.5 2043.57   323.5 2045.44
   327.5  2046.6   331.5  2046.9   335.5 2047.75   343.5 2052.02   346.7 2052.76
#Mann= 3 ,-1,0
       0      .1       0   198.8    .045       0   213.3      .1       0
Bank Sta=198.8,213.3
XS Rating Curve= 0 ,0
Exp/Cntr(USF)=0,0
Exp/Cntr=0.3,0.1

Type RM Length L Ch R = 1 ,19791   ,149.5,156.9,163
XS GIS Cut Line= 4
  2183021.761741658354.905000586 2183023.7001015658251.581711394
 2183023.7001015658042.8916919672183021.95374151657971.290932163
#Sta/Elev= 30
       0 2042.49    13.7 2041.74    37.7 2039.35    45.7 2038.73    69.7 2037.98
    77.7  2037.5    85.7 2036.63   101.2 2036.36   109.7 2036.39   121.3 2035.51
   154.2 2035.37   177.7 2035.56   185.7 2034.92   205.7 2034.72   239.82035.026
   249.7 2034.68   254.52034.785   261.3 2035.12   265.3 2035.53   273.7 2037.11
   297.7 2039.58   317.7 2040.73   321.7 2040.66   333.8 2041.02   341.8 2041.53
   345.8 2041.25   349.8 2041.22   361.8 2041.74   377.8 2043.36   383.7 2044.44
#Mann= 3 ,-1,0
       0      .1       0   239.8    .045       0   254.5      .1       0
Bank Sta=239.8,254.5
XS Rating Curve= 0 ,0
Exp/Cntr=0.3,0.1

Type RM Length L Ch R = 1 ,19634   ,130,135,133.5
XS GIS Cut Line= 4
2183056.94367445658348.8158197962183070.47518732 658327.16539921
2183210.52634548658095.7765292032183223.18775677658025.464902539
#Sta/Elev= 30
       0 2041.13    18.4 2040.24    60.3 2036.42    77.7 2034.36   121.1 2033.75
   168.1 2034.03   172.8 2033.92   177.62033.465   183.3 2032.99   186.8 2033.07
   191.5 2033.54     203 2033.54   214.9 2033.95   240.8 2033.55   247.6 2033.64
   260.6 2034.74   278.7 2036.91   291.5 2037.65   294.4 2037.61   298.6 2038.03
   310.8 2041.57   314.9  2042.1     319 2041.61     323 2040.35   327.1 2040.08
   331.2 2040.55   339.3 2041.92   351.5 2042.63   359.6 2042.89   367.4 2042.11
#Mann= 5 ,-1,0
       0      .1       0   177.6    .045       0   191.5      .1       0
  265.53     .08       0     366      .1       0
Bank Sta=177.6,191.5
XS Rating Curve= 0 ,0
Exp/Cntr=0.3,0.1

Type RM Length L Ch R = 1 ,19499   ,36.9,38.6,40.3
XS GIS Cut Line= 5
2183113.09945285658345.4329415792183222.70470706658292.660041402
2183249.09115715658260.8609861672183260.59294309658229.738506576
 2183259.2397918658010.527998148
#Sta/Elev= 30
       0 2039.93    34.5 2038.18    65.6 2035.45    83.4 2034.95     128 2034.41
   133.7 2034.16   140.22033.175   142.7 2032.63     149 2032.22   156.4 2032.97
   179.7  2034.1     190 2034.21   216.7 2036.04   224.7 2036.09   228.7 2036.54
   232.7 2036.24   236.5 2035.33   240.6 2034.91   260.7 2035.84   268.7 2035.72
   296.7  2038.4   300.9 2038.54   312.7 2037.57     317 2038.18   332.7 2039.42
   357.3 2039.89     376 2041.14   391.9 2041.44   404.7 2042.53   415.4 2042.98
#Mann= 5 ,-1,0
       0      .1       0   140.2    .045       0   156.4      .1       0
  296.15     .08       0  396.15      .1       0
Bank Sta=140.2,156.4
XS Rating Curve= 0 ,0
Exp/Cntr(USF)=0,0
Exp/Cntr=0.3,0.1

Type RM Length L Ch R = 1 ,19461   ,41.1,32.7,26
XS GIS Cut Line= 6
  2183127.984117658380.6148750312183222.02813142658334.607731287
2183250.44430844658314.310461988 2183279.5370611658287.247436256
2183290.36227139658242.593443798 2183289.0091201658026.089237944
#Sta/Elev= 30
       0 2043.53      18 2043.53    35.1 2039.45    41.6 2038.28    62.4 2038.06
    80.6  2036.8   104.7 2036.42   112.2 2035.76   122.1 2033.72   147.4 2033.38
   156.12032.766   163.8 2032.22   169.3 2032.75   189.7 2034.46   206.2 2035.14
   230.7 2035.86   240.8 2035.68   262.7 2036.56   286.7 2036.32   302.7 2038.17
   310.7 2037.88   322.7 2039.33   330.7 2039.06   345.3 2040.21   378.7 2041.96
   387.9 2043.38   417.7 2046.33   430.7 2046.61   438.7 2045.32   441.8  2045.7
#Mann= 5 ,-1,0
       0      .1       0   156.1    .045       0   169.3      .1       0
   345.3     .08       0  441.81      .1       0
Bank Sta=156.1,169.3
XS Rating Curve= 0 ,0
Exp/Cntr(USF)=0,0
Exp/Cntr=0.3,0.1

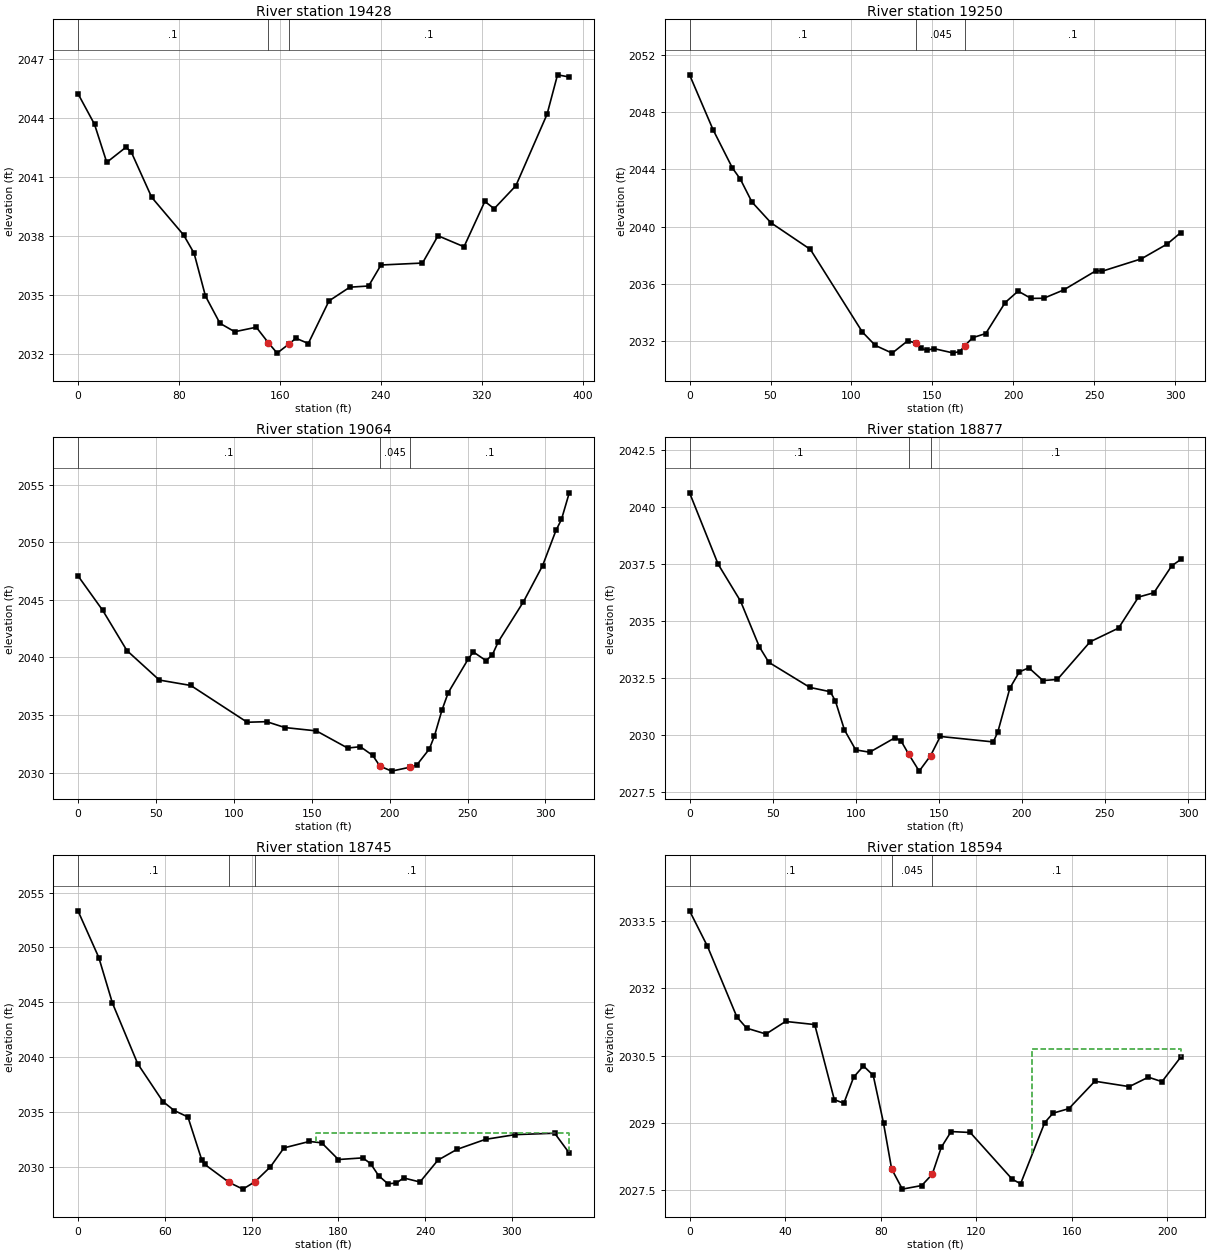
Type RM Length L Ch R = 1 ,19428   ,182.6,178.3,169
XS GIS Cut Line= 3
 2183252.4635285658473.7166173062183274.12445595658398.205841757
2183346.88886076 658096.11564772
#Sta/Elev= 30
       0 2045.25    13.1 2043.69    22.8 2041.75      38 2042.52    42.2 2042.28
    58.4 2039.97    83.7 2038.05      92 2037.12     101 2034.94   112.5 2033.55
   124.2 2033.12   141.3 2033.35   150.7 2032.57   157.8 2032.03   167.3  2032.5
   172.7 2032.79   182.5 2032.52   198.9 2034.69   215.4 2035.39   230.3 2035.45
   240.1 2036.52     273 2036.62   285.3 2038.01   305.9 2037.45   322.4 2039.76
   329.8 2039.39     347 2040.56   371.7  2044.2     380 2046.21   389.3  2046.1
#Mann= 3 ,-1,0
       0      .1       0   150.7    .045       0   167.3      .1       0
Bank Sta=150.7,167.3
XS Rating Curve= 0 ,0
Exp/Cntr=0.3,0.1

Type RM Length L Ch R = 1 ,19250   ,183,185.5,177.1
XS GIS Cut Line= 4
 2183462.5746571658523.6256895962183459.62407222658467.230318272
2183448.12149285 658310.370221392183444.58905792658220.823139541
#Sta/Elev= 30
       0 2050.62    14.5 2046.78    26.5 2044.09    31.3 2043.33    38.5 2041.72
    50.3 2040.26    74.6  2038.4   106.7 2032.62   114.7 2031.68   125.1 2031.14
   134.7    2032   140.1 2031.84   142.8 2031.47   146.8 2031.34   150.8 2031.46
   162.8 2031.15   166.8 2031.25     170 2031.66   174.8 2032.22   182.9 2032.51
   194.9 2034.68   202.9 2035.48   210.9 2034.97   218.7 2034.98     231 2035.56
     251 2036.91     255 2036.88     279 2037.74     295 2038.78   303.4 2039.58
#Mann= 3 ,-1,0
       0      .1       0   140.1    .045       0     170      .1       0
Bank Sta=140.1,170
XS Rating Curve= 0 ,0
Exp/Cntr=0.3,0.1

Type RM Length L Ch R = 1 ,19064   ,167.7,187,192.6
XS GIS Cut Line= 3
2183631.29817026658489.0098014142183597.88702739658217.080221872
2183591.39041627658176.244380576
#Sta/Elev= 30
       0 2047.08    15.9 2044.08    31.4  2040.6    52.2 2038.04    72.4 2037.57
   108.6 2034.38   121.1 2034.43   132.8 2033.92     153 2033.63   173.1 2032.14
   181.2 2032.26   189.2  2031.5   193.8 2030.57   201.3 2030.14   213.4 2030.49
   217.5 2030.68   225.5 2032.06   228.8  2033.2   233.6 2035.43   237.6 2036.94
   250.3 2039.83   253.7 2040.48   261.8 2039.73   265.8 2040.19   269.8 2041.37
   285.9 2044.83   298.2 2047.97   306.8 2051.03   310.3 2051.97   315.3 2054.28
#Mann= 3 ,-1,0
       0      .1       0   193.8    .045       0   213.4      .1       0
Bank Sta=193.8,213.4
XS Rating Curve= 0 ,0
Exp/Cntr=0.3,0.1

Type RM Length L Ch R = 1 ,18877   ,132.8,132,128.8
XS GIS Cut Line= 3
2183665.40144475658457.5283162662183813.95728559658273.399920344
2183853.04832276658229.046628172
#Sta/Elev= 30
       0 2040.61    17.2 2037.48    30.7 2035.86      42 2033.86    47.7 2033.18
    72.4 2032.08    84.7 2031.89    87.8 2031.48    93.2 2030.22     100 2029.34
   108.4 2029.24   123.8 2029.88   127.4 2029.72   131.92029.152   138.2 2028.41
   145.12029.092   150.9 2029.93   182.8 2029.69   185.5 2030.12   192.8 2032.05
   198.5 2032.76   204.2 2032.94   212.7 2032.38   221.4 2032.43   241.1 2034.08
   258.2 2034.68   270.2 2036.04   279.5 2036.23   290.2 2037.41   295.7 2037.69
#Mann= 3 ,-1,0
       0      .1       0   131.9    .045       0   145.1      .1       0
Bank Sta=131.9,145.1
XS Rating Curve= 0 ,0
Exp/Cntr=0.3,0.1

Type RM Length L Ch R = 1 ,18745   ,155.4,150.9,144.2
XS GIS Cut Line= 3
2183783.21232835658529.2806652432183867.78428376658396.671839157
2183999.03995856 658270.15219386
#Sta/Elev= 30
       0 2053.34    14.4 2049.08    23.8 2044.93    41.3 2039.39    58.7 2035.95
    66.5 2035.13      76 2034.54    85.5 2030.65    87.7 2030.21   104.5 2028.57
     114 2027.96   122.4 2028.64     133 2029.99   142.4 2031.72     160 2032.31
   168.5 2032.18     180 2030.66   196.9 2030.81   202.3 2030.28   207.8 2029.19
   214.2 2028.45     220 2028.51   225.1 2028.98   236.4 2028.61   248.8  2030.6
   261.9 2031.58   281.7  2032.5   302.3 2032.93   329.5 2033.06   339.6 2031.25
#Mann= 3 ,-1,0
       0      .1       0   104.5    .045       0   122.4      .1       0
#XS Ineff= 2 , 0
                         164.733         2033.08
Permanent Ineff=
       F       T
Bank Sta=104.5,122.4
XS Rating Curve= 0 ,0
Exp/Cntr(USF)=0,0
Exp/Cntr=0.3,0.1

Type RM Length L Ch R = 1 ,18594   ,119.9,131.6,152.4
XS GIS Cut Line= 3
2183968.24697131658548.5847214972183990.44203529658436.129730674
2184046.17630705658364.119078655
#Sta/Elev= 30
       0 2033.72     7.5 2032.93    19.8 2031.36    23.9 2031.11      32 2030.98
    40.2 2031.26    52.4 2031.19    60.6 2029.52    64.6 2029.44    68.7 2030.02
    72.8 2030.27    76.9 2030.06    81.2    2029    84.6 2027.98    89.1 2027.53
    97.2 2027.61   101.6 2027.86   105.4 2028.46   109.5 2028.81   117.5 2028.79
   135.1 2027.75   138.6 2027.65   148.7 2029.01   152.2 2029.22   158.8 2029.32
   169.7 2029.93   184.1 2029.81   192.1 2030.02   197.8 2029.92   205.7 2030.47
#Mann= 3 ,-1,0
       0      .1       0    84.6    .045       0   101.6      .1       0
#XS Ineff= 2 , 0
                          143.52         2030.65
Permanent Ineff=
       F       F
Bank Sta=84.6,101.6
XS Rating Curve= 0 ,0
Exp/Cntr(USF)=0,0
Exp/Cntr=0.3,0.1

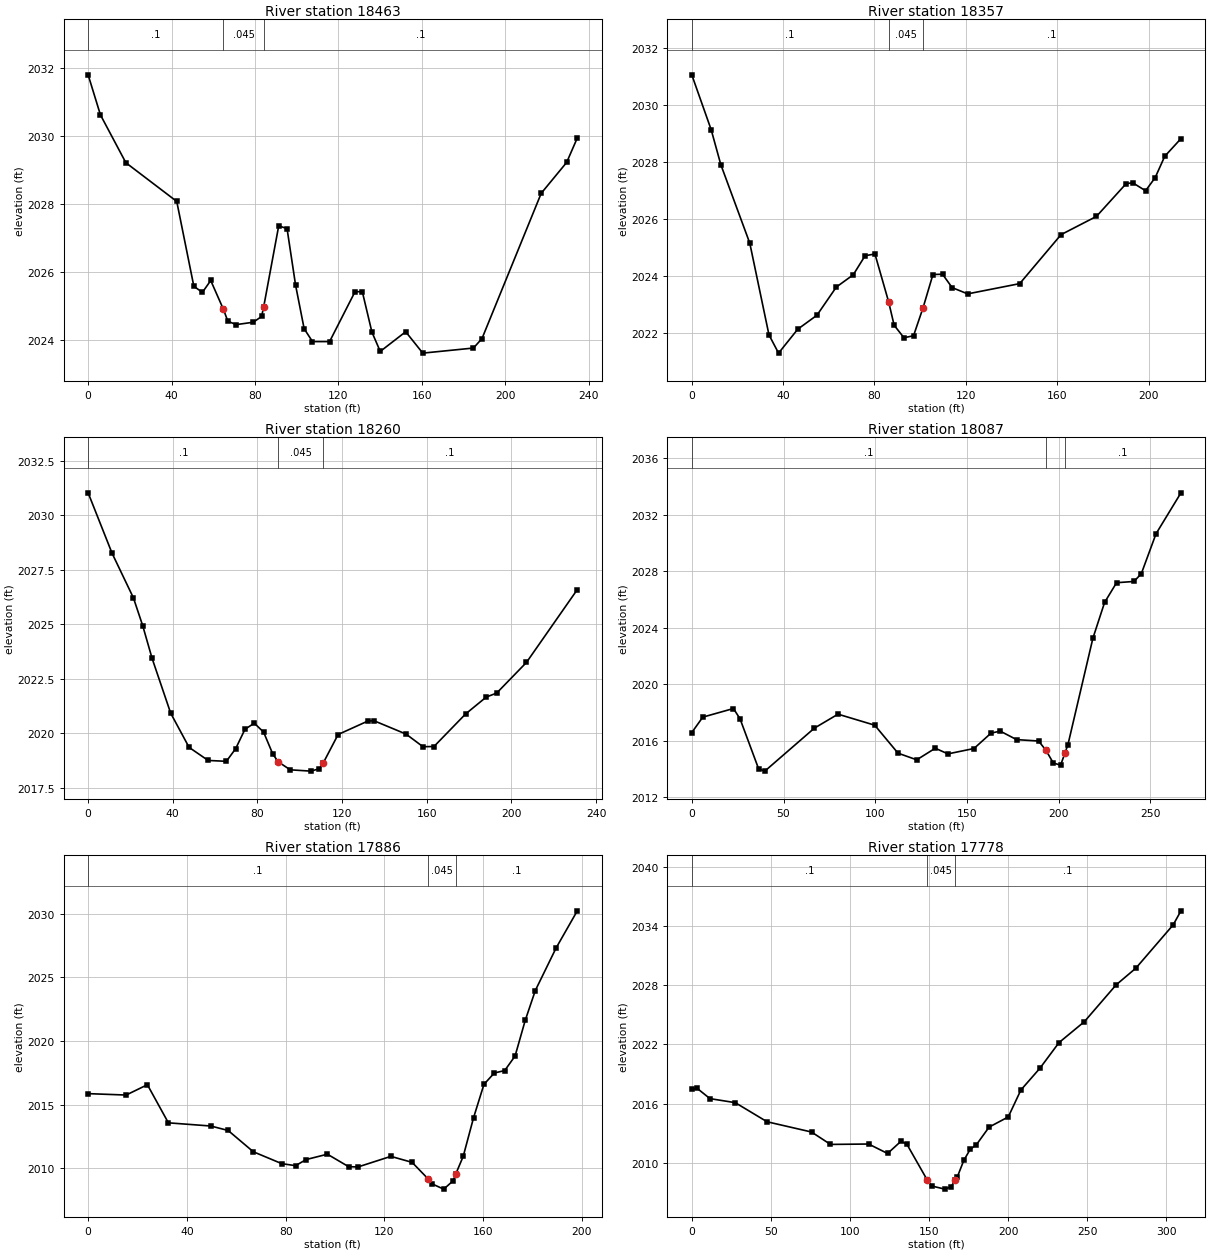
Type RM Length L Ch R = 1 ,18463   ,106.2,105.2,100.5
XS GIS Cut Line= 3
2183990.34956995 658568.517842752184088.00785145658550.268567923
2184221.17823532658526.593833013
#Sta/Elev= 30
       0 2031.81     5.9 2030.63    18.1 2029.22    42.5 2028.08    50.7 2025.58
    54.8  2025.4    58.8 2025.75    64.92024.898      67 2024.55      71 2024.45
    79.2 2024.52    83.2 2024.69    84.22024.975    91.4 2027.36    95.4 2027.28
    99.5 2025.61   103.6 2024.33   107.6 2023.95   115.8 2023.95     128 2025.42
   131.5 2025.42   136.1 2024.23   140.1 2023.66   152.3 2024.24   160.5 2023.61
   184.8 2023.76   188.9 2024.04   217.3 2028.32   229.5 2029.23   234.6 2029.95
#Mann= 3 ,-1,0
       0      .1       0    64.9    .045       0    84.2      .1       0
Bank Sta=64.9,84.2
XS Rating Curve= 0 ,0
Exp/Cntr(USF)=0,0
Exp/Cntr=0.3,0.1

Type RM Length L Ch R = 1 ,18357   ,98.9,97.7,96.1
XS GIS Cut Line= 3
2184024.10595852658674.152274514 2184091.1843741658651.957210535
2184226.82087619658605.100964359
#Sta/Elev= 30
       0 2031.05     8.5 2029.12    12.7  2027.9    25.4 2025.14    33.8 2021.92
      38 2021.28    46.4 2022.12    54.8 2022.61    63.3  2023.6    70.7 2024.03
    75.9  2024.7    80.2 2024.76    86.2 2023.08    88.6 2022.26    92.9 2021.82
    97.1 2021.89   101.3 2022.88   105.6 2024.04   109.8 2024.05     114 2023.58
   120.8 2023.36   143.6 2023.72   161.7 2025.44   177.2 2026.08   190.2 2027.23
   193.1 2027.26   198.7 2026.98   202.9 2027.44   207.1 2028.19   214.2 2028.81
#Mann= 3 ,-1,0
       0      .1       0    86.2    .045       0   101.3      .1       0
Bank Sta=86.2,101.3
XS Rating Curve= 0 ,0
Exp/Cntr(USF)=0,0
Exp/Cntr=0.3,0.1

Type RM Length L Ch R = 1 ,18260   ,177,172.9,175.3
XS GIS Cut Line= 3
2184052.71292987658776.742792458  2184173.059499658721.994967978
2184256.41429483 658668.72681443
#Sta/Elev= 30
       0 2031.03    11.3 2028.26    21.4 2026.21    25.8 2024.93    30.2 2023.44
      39 2020.92    47.7 2019.35    56.7 2018.75    65.3 2018.71    69.7 2019.29
    74.1 2020.18    78.5 2020.46    82.9 2020.05    87.3 2019.03    89.9 2018.68
    95.5 2018.32   105.2 2018.26   109.3 2018.37     111 2018.62   118.1 2019.94
   132.2 2020.56   135.1 2020.57   150.2 2019.96   158.2 2019.38   163.4 2019.39
   178.3 2020.88   188.1 2021.66     193 2021.84   207.1 2023.25   231.1 2026.59
#Mann= 3 ,-1,0
       0      .1       0    89.9    .045       0     111      .1       0
Bank Sta=89.9,111
XS Rating Curve= 0 ,0
Exp/Cntr(USF)=0,0
Exp/Cntr=0.3,0.1

Type RM Length L Ch R = 1 ,18087   ,202.6,200.6,196.1
XS GIS Cut Line= 3
2184119.43456456658888.3362017882184255.07106665 658782.78634198
2184349.77000629658784.266012911
#Sta/Elev= 30
       0 2016.59       6 2017.68    22.7 2018.29    26.3 2017.56    36.4 2014.03
    39.8 2013.86    66.8  2016.9    79.7 2017.89    99.7 2017.11   112.4 2015.13
   122.6 2014.66   132.7 2015.48   139.6 2015.08   153.8 2015.46   163.1 2016.55
   168.1 2016.69     177 2016.09     189 2015.99     193 2015.34     197 2014.44
     201 2014.28   203.32015.114     205 2015.73   218.6 2023.26     225  2025.8
   231.5 2027.19     241 2027.28     245 2027.83     253 2030.65   266.6 2033.55
#Mann= 3 ,-1,0
       0      .1       0     193    .045       0   203.3      .1       0
Bank Sta=193,203.3
XS Rating Curve= 0 ,0
Exp/Cntr(USF)=0,0
Exp/Cntr=0.3,0.1

Type RM Length L Ch R = 1 ,17886   ,105.3,107.9,109.8
XS GIS Cut Line= 4
2184209.82657401659016.1929860812184325.73413034 658971.30963448
2184372.59037651658957.0061488052184396.75833507658951.580688722
#Sta/Elev= 30
       0 2015.87    15.4 2015.76      24 2016.57    32.5 2013.58    49.7 2013.33
    56.7 2012.98    66.9 2011.31    78.4 2010.38      84 2010.22    88.3  2010.7
    96.9 2011.12   105.5 2010.14   109.3 2010.12   122.6 2010.95   131.2 2010.48
   137.6  2009.2   139.4 2008.78     144 2008.38   147.8 2009.03   148.8 2009.53
   151.9 2010.95   156.1 2013.99   160.3  2016.6   164.5 2017.49   168.7 2017.68
   172.9 2018.82     177 2021.61   181.1 2023.96   189.5 2027.29   198.1 2030.21
#Mann= 3 ,-1,0
       0      .1       0   137.6    .045       0   148.8      .1       0
Bank Sta=137.6,148.8
XS Rating Curve= 0 ,0
Exp/Cntr(USF)=0,0
Exp/Cntr=0.3,0.1

Type RM Length L Ch R = 1 ,17778   ,160.5,160.4,161
XS GIS Cut Line= 2
2184196.73142366659084.0691078552184505.06264961 659059.32011313
#Sta/Elev= 30
       0 2017.48     3.5 2017.53    11.5  2016.5    27.5 2016.09    47.6 2014.15
    75.7 2013.11    87.7 2011.85   111.8 2011.89   123.8 2010.93   132.2 2012.16
   135.9  2011.9     149  2008.2   151.9 2007.62     160 2007.31     164 2007.56
   166.4  2008.2     168 2008.59     172 2010.23     176 2011.34     180 2011.83
     188 2013.61   200.1 2014.64   208.1 2017.38   220.1 2019.58   232.2 2022.19
   248.2 2024.31   268.3 2028.05   280.8 2029.75   304.4 2034.15   309.3 2035.57
#Mann= 3 ,-1,0
       0      .1       0     149    .045       0   166.4      .1       0
Bank Sta=149,166.4
XS Rating Curve= 0 ,0
Exp/Cntr=0.3,0.1

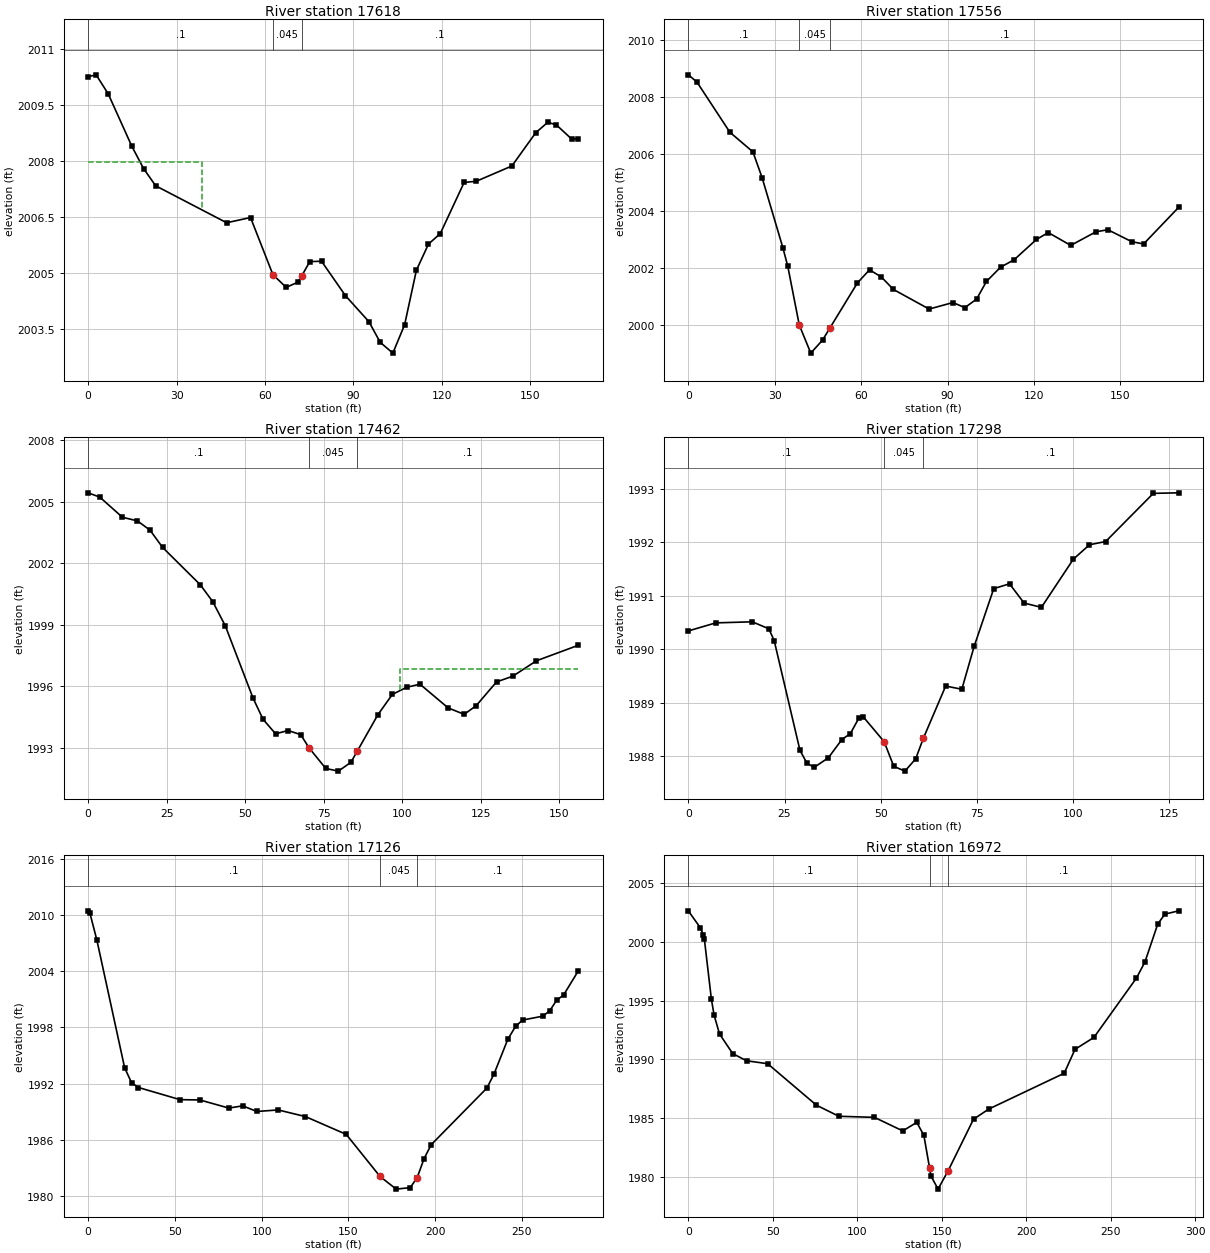
Type RM Length L Ch R = 1 ,17618   ,60.8,61.8,60.7
XS GIS Cut Line= 3
2184281.45805762659236.1186659822184398.06857554659222.794573403
2184446.47485703659214.806533217
#Sta/Elev= 30
       0 2010.25     2.7  2010.3     6.8 2009.79    14.8 2008.39    18.8 2007.79
    22.9 2007.33      47 2006.34    55.1 2006.48    62.7 2004.95    67.2 2004.61
    71.2 2004.75    72.5 2004.92    75.2  2005.3    79.2 2005.31    87.3 2004.39
    95.3 2003.69    99.1 2003.14   103.4 2002.85   107.4 2003.61   111.4 2005.07
   115.5 2005.77   119.5 2006.05   127.6 2007.42   131.7 2007.45   143.8 2007.86
   151.9 2008.75     156 2009.03   158.9 2008.96   164.1 2008.58   166.4 2008.59
#Mann= 3 ,-1,0
       0      .1       0    62.7    .045       0    72.5      .1       0
#XS Ineff= 2 , 0
           38.54 2007.97
Permanent Ineff=
       T       F
Bank Sta=62.7,72.5
XS Rating Curve= 0 ,0
Exp/Cntr=0.3,0.1

Type RM Length L Ch R = 1 ,17556   ,90.6,94.2,94.3
XS GIS Cut Line= 4
2184301.81146928659288.4672544672184321.27145196659289.090297434
 2184357.2771096659284.7020370632184467.92735428659255.087665316
#Sta/Elev= 30
       0 2008.79       3 2008.53    14.4 2006.77    22.4 2006.08    25.6 2005.17
    32.8 2002.71    34.5 2002.06    38.5 1999.99    42.5    1999    46.6 1999.46
    49.21999.893    58.7 2001.47    62.9 2001.93      67 2001.68    71.2 2001.24
    83.6 2000.55    91.9 2000.78      96  2000.6   100.1  2000.9   103.5 2001.52
   108.4 2002.02   113.2 2002.29   120.9    2003     125 2003.24   132.8 2002.79
   141.6 2003.27   145.7 2003.34     154 2002.92   158.1 2002.84   170.3 2004.13
#Mann= 3 ,-1,0
       0      .1       0    38.5    .045       0    49.2      .1       0
Bank Sta=38.5,49.2
XS Rating Curve= 0 ,0
Exp/Cntr(USF)=0,0
Exp/Cntr=0.3,0.1

Type RM Length L Ch R = 1 ,17462   ,189.1,164.3,140.8
XS GIS Cut Line= 3
2184312.51287965659361.8602492912184399.89262399659362.164708331
2184459.87105476659328.369754947
#Sta/Elev= 30
       0 2005.44     3.7 2005.23    10.9 2004.25    15.7 2004.07    19.7 2003.62
    23.7 2002.78    35.7 2000.96    39.7 2000.13    43.7 1998.95    52.5 1995.44
    55.7  1994.4    59.7 1993.69    63.7 1993.85    67.7 1993.65    70.41992.997
    75.7    1992    79.7 1991.87    83.7  1992.3    85.81992.863    92.3 1994.62
    96.9 1995.61   101.5 1995.96   105.7 1996.11   114.7 1994.95   119.8 1994.64
   123.6 1995.06   130.1 1996.22   135.3  1996.5   142.8 1997.25   156.2 1998.01
#Mann= 3 ,-1,0
       0      .1       0    70.4    .045       0    85.8      .1       0
#XS Ineff= 2 , 0
                           99.43         1996.83
Permanent Ineff=
       F       F
Bank Sta=70.4,85.8
XS Rating Curve= 0 ,0
Exp/Cntr=0.3,0.1

Type RM Length L Ch R = 1 ,17298   ,158.1,171.6,177.6
XS GIS Cut Line= 3
2184506.43872651659494.3995236212184461.61633192659446.274426279
2184444.86691079659386.825776621
#Sta/Elev= 30
       0 1990.34     7.1 1990.49    16.6 1990.51    20.9 1990.38    22.3 1990.16
      29 1988.11    30.8 1987.87    32.7 1987.79    36.4 1987.97    39.9 1988.31
    42.1 1988.42    44.4 1988.72    45.4 1988.74    50.9 1988.27    53.4 1987.81
    56.3 1987.72    59.1 1987.95    61.11988.335    66.9 1989.31    71.1 1989.25
    74.3 1990.05    79.4 1991.13    83.5 1991.22    87.3 1990.86    91.8 1990.78
   100.1 1991.68   104.3 1991.95   108.5 1992.01   120.9 1992.91   127.5 1992.92
#Mann= 3 ,-1,0
       0      .1       0    50.9    .045       0    61.1      .1       0
Bank Sta=50.9,61.1
XS Rating Curve= 0 ,0
Exp/Cntr(USF)=0,0
Exp/Cntr=0.3,0.1

Type RM Length L Ch R = 1 ,17126   ,145.3,154.1,159.2
XS GIS Cut Line= 4
2184623.25371301659566.1295287152184618.24204158 659479.26055723
2184600.90743319659320.6710614492184598.22384868659284.604235387
#Sta/Elev= 30
       0 2010.46       1 2010.21       5 2007.34      21  1993.7      25 1992.09
      29 1991.58      53 1990.28    64.4 1990.25    81.1 1989.38    89.1 1989.62
    97.2 1989.02   109.6 1989.18   125.3 1988.47   148.8 1986.57   168.3 1982.07
   177.6 1980.72   185.7 1980.88   189.7 1981.95   193.7 1983.99   197.8 1985.47
   229.9 1991.52     234 1993.02     242 1996.75   246.5 1998.13   250.5 1998.79
   262.1  1999.2   266.1 1999.77   270.1  2000.9   274.1 2001.46   282.7 2004.07
#Mann= 3 ,-1,0
       0      .1       0   168.3    .045       0   189.7      .1       0
Bank Sta=168.3,189.7
XS Rating Curve= 0 ,0
Exp/Cntr=0.3,0.1

Type RM Length L Ch R = 1 ,16972   ,155.2,148.2,148.7
XS GIS Cut Line= 3
 2184702.0658555  659578.16372742184776.48917626659342.114002962
2184789.51729097659301.376912673
#Sta/Elev= 30
       0 2002.59       7 2001.19     8.8 2000.57     9.4 2000.26    13.6 1995.11
    15.2 1993.76    18.4 1992.17    26.2  1990.5    34.4 1989.89    46.9 1989.64
    75.8 1986.12    89.1 1985.18   110.1 1985.09   126.9 1983.94   135.2 1984.66
   139.4 1983.57   142.8 1980.78   143.6 1980.12   147.8    1979   153.81980.566
   168.8 1984.93   177.8 1985.79   222.5 1988.83   228.9 1990.86   240.1 1991.87
   265.3 1996.91   270.3 1998.27   277.9 2001.49   282.1 2002.33   290.3 2002.61
#Mann= 3 ,-1,0
       0      .1       0   142.8    .045       0   153.8      .1       0
Bank Sta=142.8,153.8
XS Rating Curve= 0 ,0
Exp/Cntr=0.3,0.1

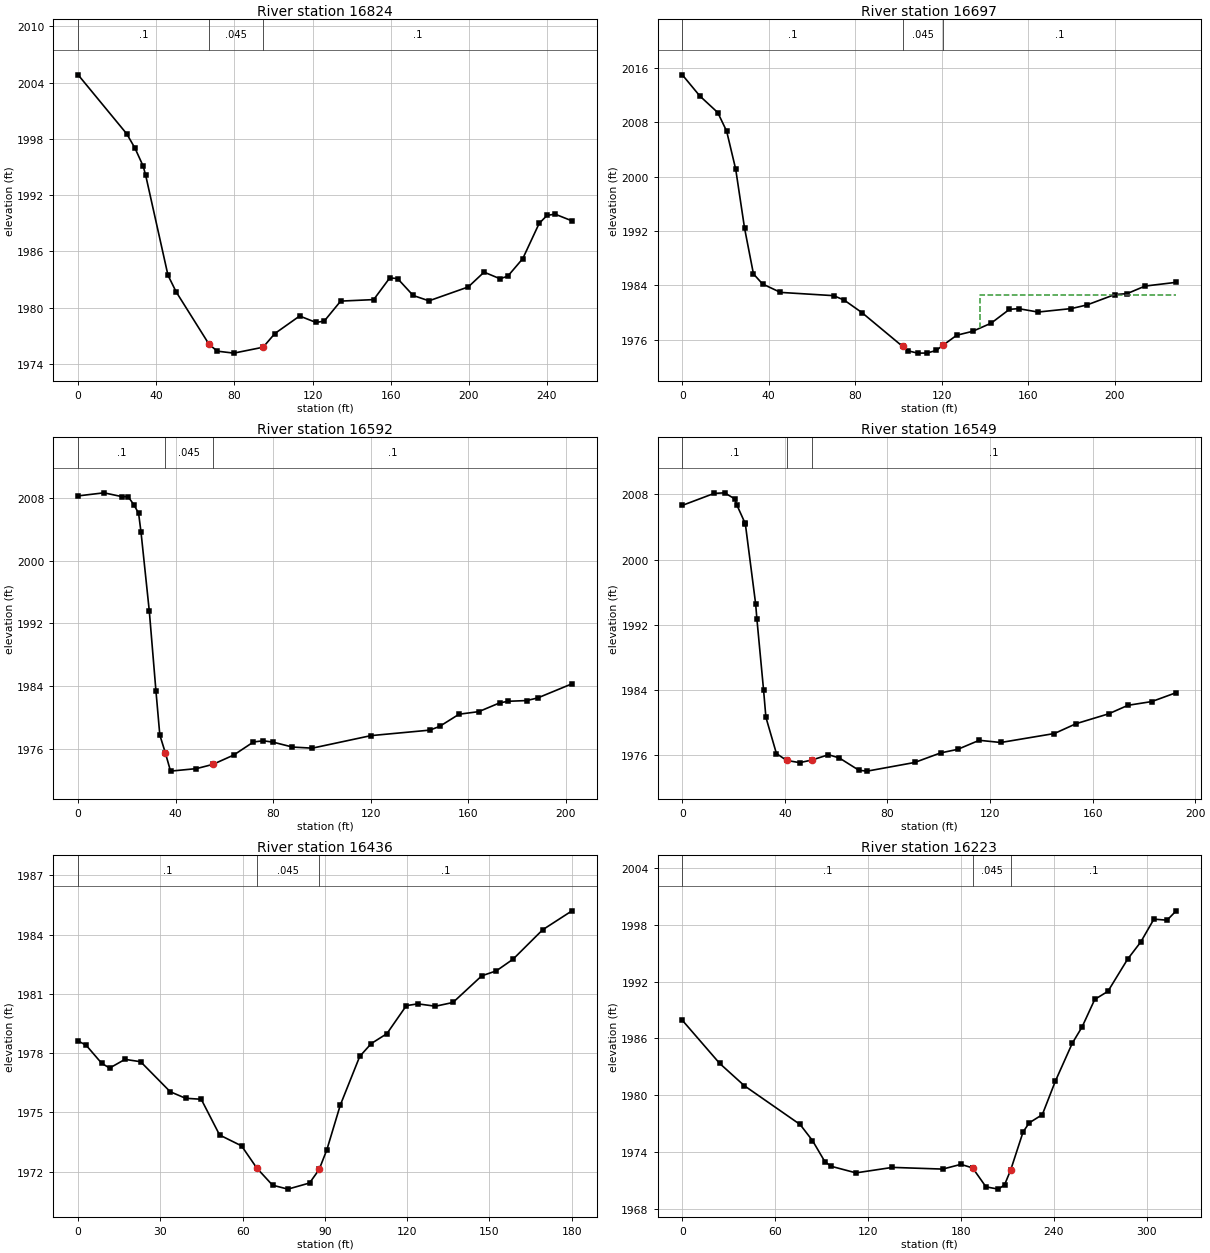
Type RM Length L Ch R = 1 ,16824   ,134.9,126.9,129.9
XS GIS Cut Line= 3
2184836.16958671659608.8308201352184884.49987972659462.454554738
 2184872.8134584659364.487247183
#Sta/Elev= 30
       0 2004.84    24.9 1998.54    29.1 1997.02    33.3  1995.1    34.6 1994.11
      46 1983.46    50.2 1981.68      67  1976.1    71.2 1975.36    79.7 1975.15
    94.7 1975.78   100.7 1977.24   113.4 1979.11   121.8 1978.42     126 1978.57
   134.4  1980.7   151.3 1980.86   159.5 1983.17   163.5 1983.11   171.5  1981.3
   179.6 1980.73   199.7 1982.21   207.8 1983.79   215.9 1983.09   219.9 1983.35
   227.6 1985.23     236 1988.99     240 1989.84   244.1 1989.98   252.8 1989.26
#Mann= 3 ,-1,0
       0      .1       0      67    .045       0    94.7      .1       0
Bank Sta=67,94.7
XS Rating Curve= 0 ,0
Exp/Cntr=0.3,0.1

Type RM Length L Ch R = 1 ,16697   ,115.9,104.5,93.9
XS GIS Cut Line= 4
2184932.57354729659596.9856326822184945.79947314659547.815670808
2184985.32911749659436.1014585012185001.37013259659379.385012254
#Sta/Elev= 30
       0 2014.95     8.1 2011.84    16.4  2009.4    20.5 2006.67    24.7 2001.06
    28.8 1992.38    32.9 1985.68    37.1  1984.2    45.4 1982.96      70 1982.48
    74.9 1981.82    83.1 1979.98   101.9 1975.01   104.6 1974.35   108.9 1974.03
   113.1 1974.04   117.4 1974.42   120.7 1975.22   126.9 1976.66   134.3 1977.24
   142.8 1978.43   151.3 1980.47   155.5 1980.57   164.5 1980.07   179.9 1980.58
   187.1 1981.11     200 1982.64   205.7 1982.78     214 1983.89   228.4 1984.44
#Mann= 3 ,-1,0
       0      .1       0   101.9    .045       0   120.7      .1       0
#XS Ineff= 2 , 0
                          137.89         1982.63
Permanent Ineff=
       F       F
Bank Sta=101.9,120.7
XS Rating Curve= 0 ,0
Exp/Cntr=0.3,0.1

Type RM Length L Ch R = 1 ,16592   ,38.8,43.3,46.3
XS GIS Cut Line= 3
2185067.21353775659576.0284089552185042.85681459659519.026911005
2185029.97683219659379.107862626
#Sta/Elev= 30
       0 2008.25    10.6 2008.64    17.9 2008.16    20.5 2008.15    22.8 2007.15
    24.8 2006.04    25.8  2003.6    29.2 1993.52    31.9 1983.42    33.5 1977.75
    35.81975.436    37.9 1973.14    48.5 1973.46    55.21973.994    63.8 1975.19
    71.9 1976.86    75.9 1977.01    79.9 1976.84    87.9 1976.21      96 1976.07
   120.1 1977.67   144.2 1978.37   148.2 1978.84   156.2  1980.4   164.3 1980.73
   172.8 1981.84   176.3 1982.05   183.9 1982.14   188.4 1982.47   202.5 1984.28
#Mann= 3 ,-1,0
       0      .1       0    35.8    .045       0    55.2      .1       0
Bank Sta=35.8,55.2
XS Rating Curve= 0 ,0
Exp/Cntr(USF)=0,0
Exp/Cntr=0.3,0.1

Type RM Length L Ch R = 1 ,16549   ,120.4,113.1,100.5
XS GIS Cut Line= 4
2185095.56431154659569.5156176112185094.04201635659556.423878913
2185087.64837652659514.4085314632185045.60400743659384.131576277
#Sta/Elev= 30
       0 2006.65    12.4 2008.12    16.5 2008.19    20.5 2007.44    21.2 2006.75
    24.4 2004.52    24.6 2004.34    28.6 1994.57    29.1 1992.68    31.7 1983.98
    32.6 1980.67    36.7 1976.23    40.7 1975.38    45.8 1975.11    50.61975.437
      57 1976.08    61.2 1975.69    68.9 1974.17    72.1 1974.07    90.6 1975.13
   100.7  1976.3   107.4 1976.74   115.8 1977.85   124.2 1977.58   145.1 1978.68
   153.6 1979.89   166.3  1981.1   173.8 1982.14   183.1  1982.6   192.6 1983.69
#Mann= 3 ,0,0
       0      .1       0    40.7    .045       0    50.6      .1       0
Bank Sta=40.7,50.6
XS Rating Curve= 0 ,0
Exp/Cntr(USF)=0,0
Exp/Cntr=0.3,0.1

Type RM Length L Ch R = 1 ,16436   ,201.5,212.9,227.8
XS GIS Cut Line= 4
2185179.47851016659498.0033132362185169.34576012659485.688292871
2185078.09938599659393.9486950952185052.22042629659370.745683799
#Sta/Elev= 30
       0 1978.62     2.9 1978.41     8.6 1977.49    11.5 1977.25    17.1 1977.69
    22.8 1977.57    33.6 1976.05    39.2 1975.72    44.9 1975.67    51.6 1973.86
    59.6 1973.31    65.2 1972.18    70.9 1971.32    76.5 1971.12    84.4 1971.43
    87.91972.114    90.7 1973.11    95.6 1975.37   102.7 1977.84   106.9 1978.49
   112.6 1978.99   119.7 1980.41   123.9  1980.5   130.3 1980.38   136.7 1980.57
   147.2 1981.92   152.5 1982.17   158.6 1982.76   169.4 1984.25   180.1 1985.21
#Mann= 3 ,-1,0
       0      .1       0    65.2    .045       0    87.9      .1       0
Bank Sta=65.2,87.9
XS Rating Curve= 0 ,0
Exp/Cntr=0.3,0.1

Type RM Length L Ch R = 1 ,16223   ,340.1,331.8,310.2
XS GIS Cut Line= 4
2185318.03922727659589.3079530082185315.39187932659425.867832219
2185318.95405009659362.8448110442185288.20334814659275.589411127
#Sta/Elev= 30
       0 1987.93    24.1 1983.37    40.1    1981    76.1  1976.9    84.1  1975.2
    92.1 1972.97    96.1 1972.48   112.2 1971.78   135.8 1972.36   168.2 1972.18
     180 1972.68   187.51972.309   187.6  1972.3   196.2  1970.3   204.2 1970.06
   208.2 1970.51   212.2  1972.1   220.2 1976.12   224.2 1977.08   232.6 1977.94
   241.1 1981.51     252 1985.51   258.3 1987.22   266.5 1990.14     275 1990.99
   287.7 1994.39   296.2 1996.21   304.7 1998.63   313.2 1998.52   319.1 1999.51
#Mann= 3 ,-1,0
       0      .1       0   187.5    .045       0   212.2      .1       0
Bank Sta=187.6,212.2
XS Rating Curve= 0 ,0
Exp/Cntr=0.3,0.1