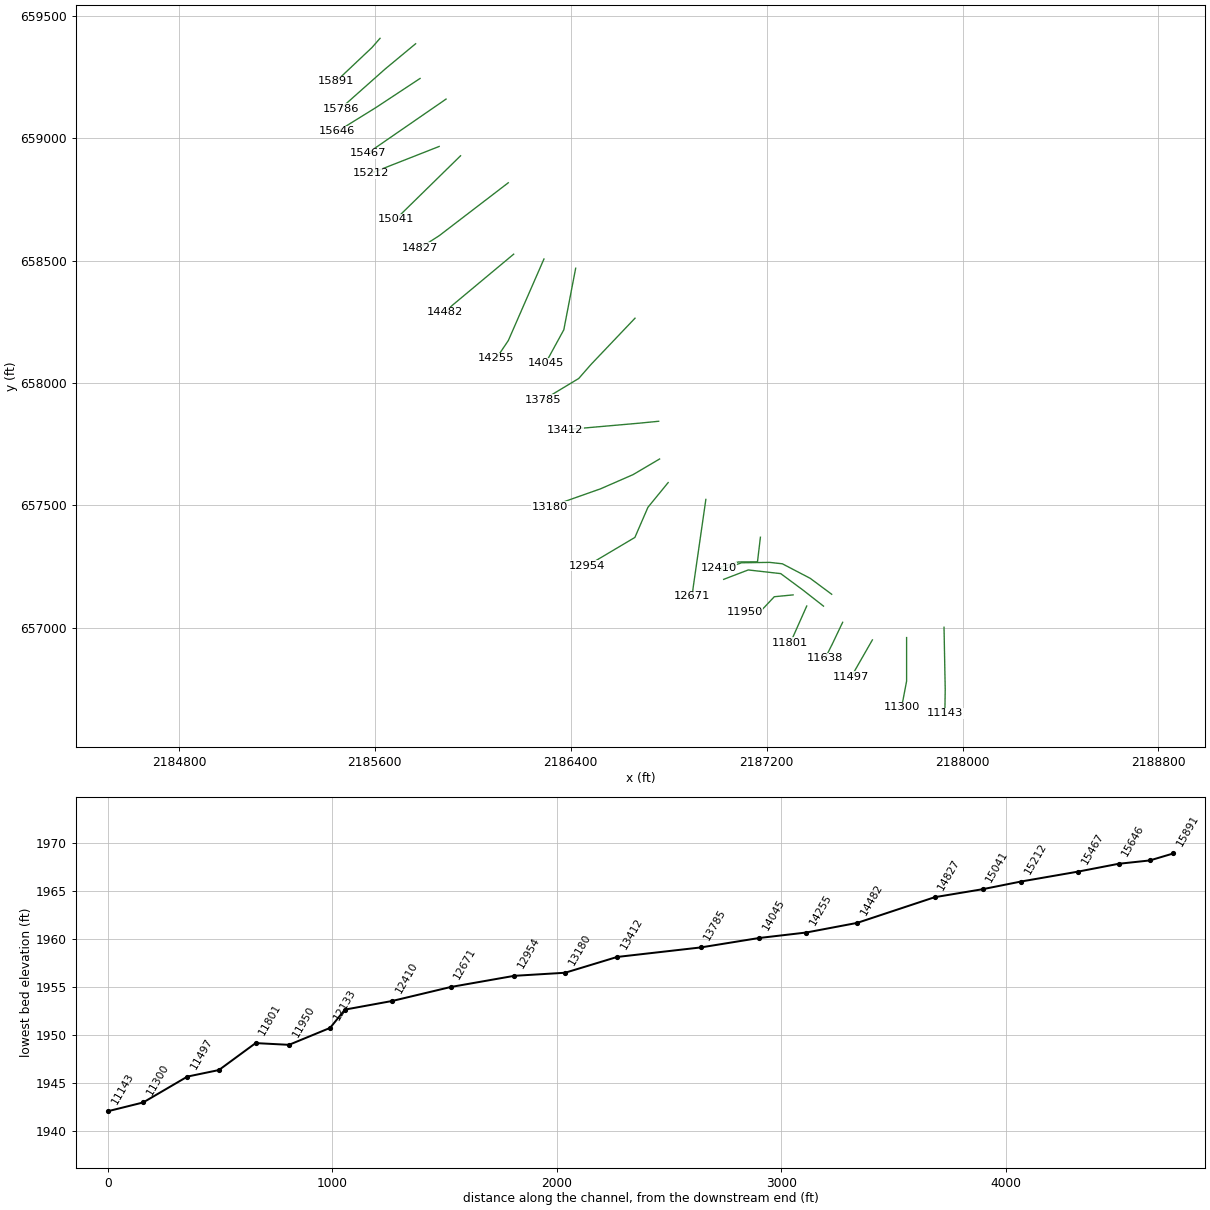
HEC-RAS study BIGRN.prj: BIGRN

--- BIGRN.g01 (geometry) --- (continued)

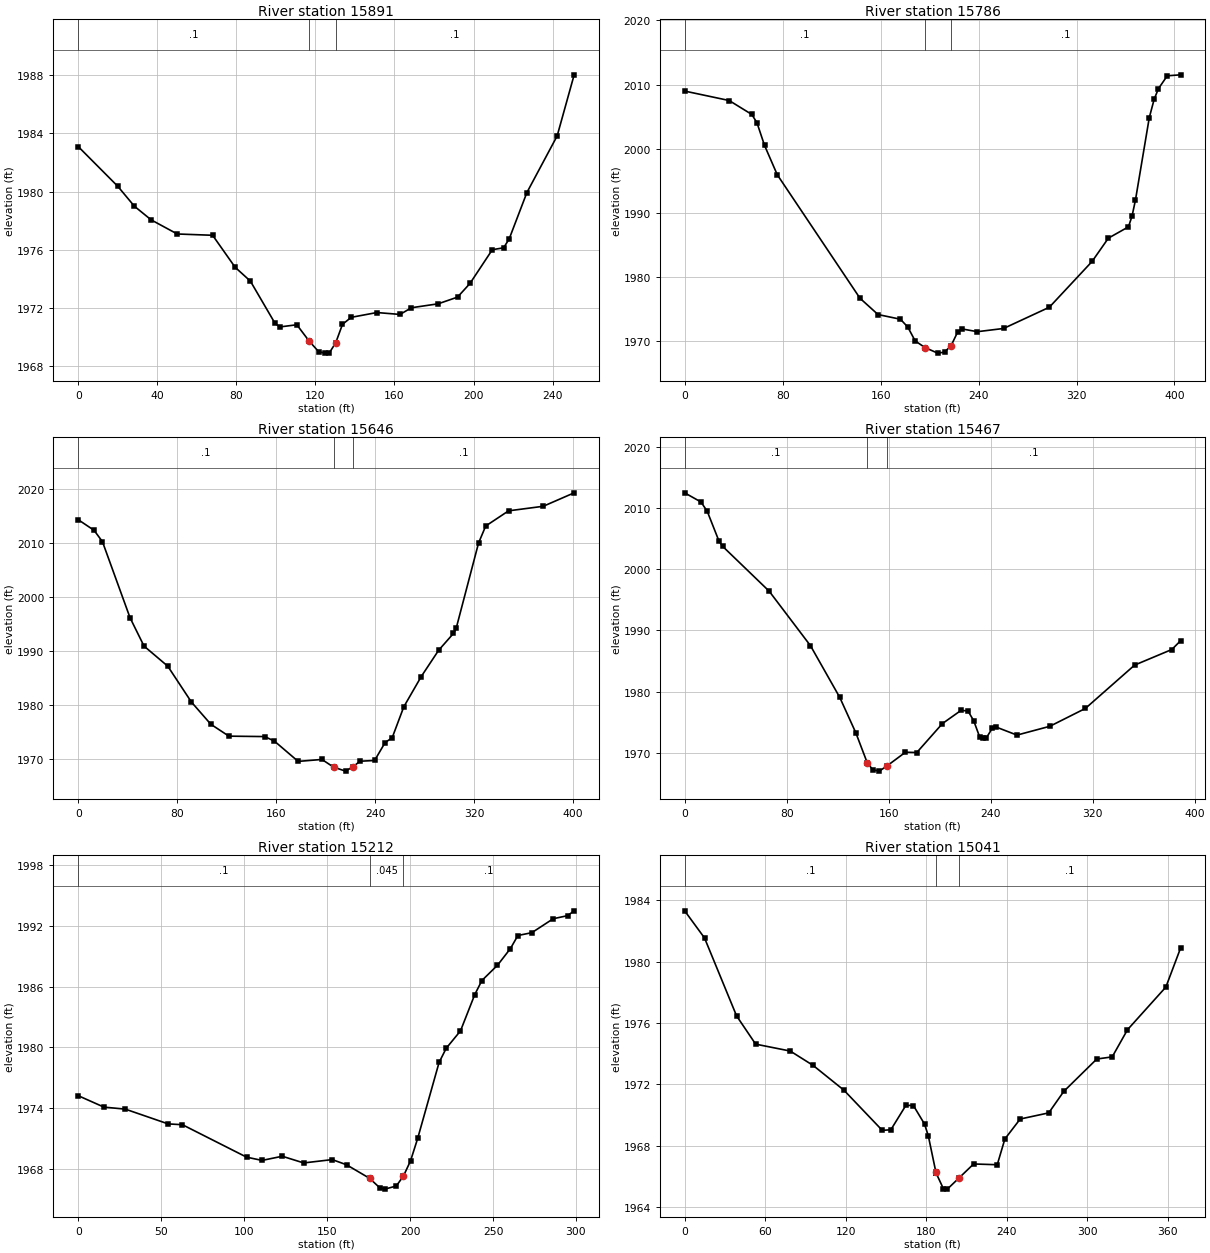
Type RM Length L Ch R = 1 ,15891   ,105.3,105.2,103.7
XS GIS Cut Line= 4
2185621.16843053659408.238912641 2185588.1697709659370.599816495
2185466.48721349 659255.620111832185441.81983218659233.023329074
#Sta/Elev= 30
       0 1983.09      20 1980.36    28.4 1978.99    36.9 1978.05    50.1 1977.08
      68 1976.99    79.4 1974.79    87.1 1973.84    99.6 1970.93     102 1970.69
   110.6 1970.84   116.91969.705   121.6    1969   124.6 1968.89   127.1 1968.92
   130.3 1969.61   133.7 1970.87   138.1 1971.35   151.1 1971.68   162.8 1971.55
   168.6 1972.01   182.1 1972.28   191.9 1972.74   198.2 1973.68   209.5    1976
   215.2 1976.13     218 1976.73     227 1979.93   242.3 1983.82   250.9 1988.02
#Mann= 3 ,0,0
       0      .1       0   116.9    .045       0   130.3      .1       0
Bank Sta=116.9,130.3
XS Rating Curve= 0 ,0
Exp/Cntr=0.3,0.1

Type RM Length L Ch R = 1 ,15786   ,141.4,139.5,131.3
XS GIS Cut Line= 3
2185766.37185425659386.0432118382185641.95803395659282.799483023
2185460.03436097659121.173079347
#Sta/Elev= 30
       0 2008.98    36.3 2007.51    54.8 2005.34      59 2004.06    65.2 2000.52
    75.6 1995.95   143.2  1976.7   157.9 1974.17   176.2 1973.44   182.2 1972.22
   188.2 1970.07   196.2 1969.03   206.6 1968.16   212.2 1968.31   217.6 1969.34
   222.9 1971.44   226.4 1971.93     239  1971.5   260.4    1972   297.8 1975.31
   332.7 1982.44     346 1986.07   362.4 1987.83   365.3 1989.49   368.1 1991.98
   379.4 2004.83   383.4 2007.71   386.9 2009.36   394.1 2011.36     405 2011.51
#Mann= 3 ,-1,0
       0      .1       0   196.2    .045       0   217.6      .1       0
Bank Sta=196.2,217.6
XS Rating Curve= 0 ,0
Exp/Cntr=0.3,0.1

Type RM Length L Ch R = 1 ,15646   ,178,179.7,178.7
XS GIS Cut Line= 3
2185784.56041986  659244.2543614     2185606.083      659126.438
 2185447.1898642  659027.8279672
#Sta/Elev= 30
       0 2014.32    12.8 2012.36    19.6 2010.25    41.9 1996.18    53.2 1990.94
    72.4 1987.22    91.5 1980.59   107.2 1976.48   121.8 1974.28   150.8  1974.2
   158.6 1973.36   177.8 1969.61     197 1969.97   206.41968.553   216.1 1967.81
     222  1968.6   227.8 1969.64   239.6 1969.78   248.1  1973.1   253.8 1973.98
   263.2 1979.71   277.3 1985.31   291.4 1990.18   303.3 1993.27   305.5  1994.2
   323.6 2009.99   329.4 2013.15   347.9 2015.96   375.9  2016.8   400.9 2019.29
#Mann= 3 ,-1,0
       0      .1       0   206.4    .045       0     222      .1       0
Bank Sta=206.4,222
XS Rating Curve= 0 ,0
Exp/Cntr=0.3,0.1

Type RM Length L Ch R = 1 ,15467   ,255.2,254.5,252.6
XS GIS Cut Line= 2
2185890.72093992659159.9211179362185570.47513543658938.906407792
#Sta/Elev= 30
       0 2012.49    12.8 2010.99    17.7 2009.47    26.8 2004.66    29.7 2003.76
    66.3 1996.41    98.7  1987.5   121.7 1979.04   134.3 1973.25   143.2 1968.38
   147.6 1967.22   152.7    1967   158.6 1967.83   173.2 1970.09   182.1 1970.04
   202.2 1974.77   216.9 1976.94   222.3 1976.82   226.7 1975.27   231.5 1972.55
   233.8 1972.38   236.4 1972.34   241.2 1973.97   244.3 1974.21   260.7 1972.89
   286.5 1974.33   314.4 1977.25     353 1984.33   382.2 1986.88   389.1 1988.32
#Mann= 3 ,-1,0
       0      .1       0   143.2    .045       0   158.6      .1       0
Bank Sta=143.2,158.6
XS Rating Curve= 0 ,0
Exp/Cntr=0.3,0.1

Type RM Length L Ch R = 1 ,15212   ,166.5,171.5,178.9
XS GIS Cut Line= 2
2185862.60435618658966.4167675842185584.45659171658856.995274656
#Sta/Elev= 30
       0 1975.21    15.5 1974.08    28.4 1973.88    54.2 1972.42    62.8 1972.34
   101.5 1969.13   110.8 1968.81     123 1969.22   135.9 1968.56   153.1 1968.89
   161.7 1968.38   175.6 1967.04   181.7 1966.11   184.8 1965.97   191.7 1966.28
     196 1967.26   200.3 1968.77   204.6 1970.99   217.5  1978.5   221.8  1979.9
   230.4 1981.62     239 1985.21   243.3  1986.6   252.7 1988.11   260.5 1989.76
     265 1991.05   273.4 1991.33   286.3 1992.71   294.9 1993.01   298.9 1993.49
#Mann= 3 ,-1,0
       0      .1       0   175.6    .045       0     196      .1       0
Bank Sta=175.6,196
XS Rating Curve= 0 ,0
Exp/Cntr=0.3,0.1

Type RM Length L Ch R = 1 ,15041   ,213.6,213.5,210.4
XS GIS Cut Line= 2
 2185949.9476834658928.2826915452185685.95840633658669.449455046
#Sta/Elev= 30
       0 1983.31    14.8 1981.54    38.7 1976.46    52.9 1974.62    78.7 1974.17
    95.8 1973.23   118.7 1971.62   147.3    1969   153.7 1969.04   164.9 1970.63
   170.5 1970.62   178.8 1969.41   181.6 1968.65   187.3 1966.26   187.3 1966.25
   187.3 1966.24   192.9 1965.19   195.8 1965.17   204.3 1965.88   215.4 1966.81
     233 1966.76   238.7 1968.44   250.1 1969.74   271.4 1970.14   282.6 1971.54
   307.2 1973.65   318.7 1973.79   330.1 1975.56   358.7 1978.34   369.7 1980.89
#Mann= 3 ,-1,0
       0      .1       0   187.3    .045       0   204.3      .1       0
Bank Sta=187.3,204.3
XS Rating Curve= 0 ,0
Exp/Cntr=0.3,0.1

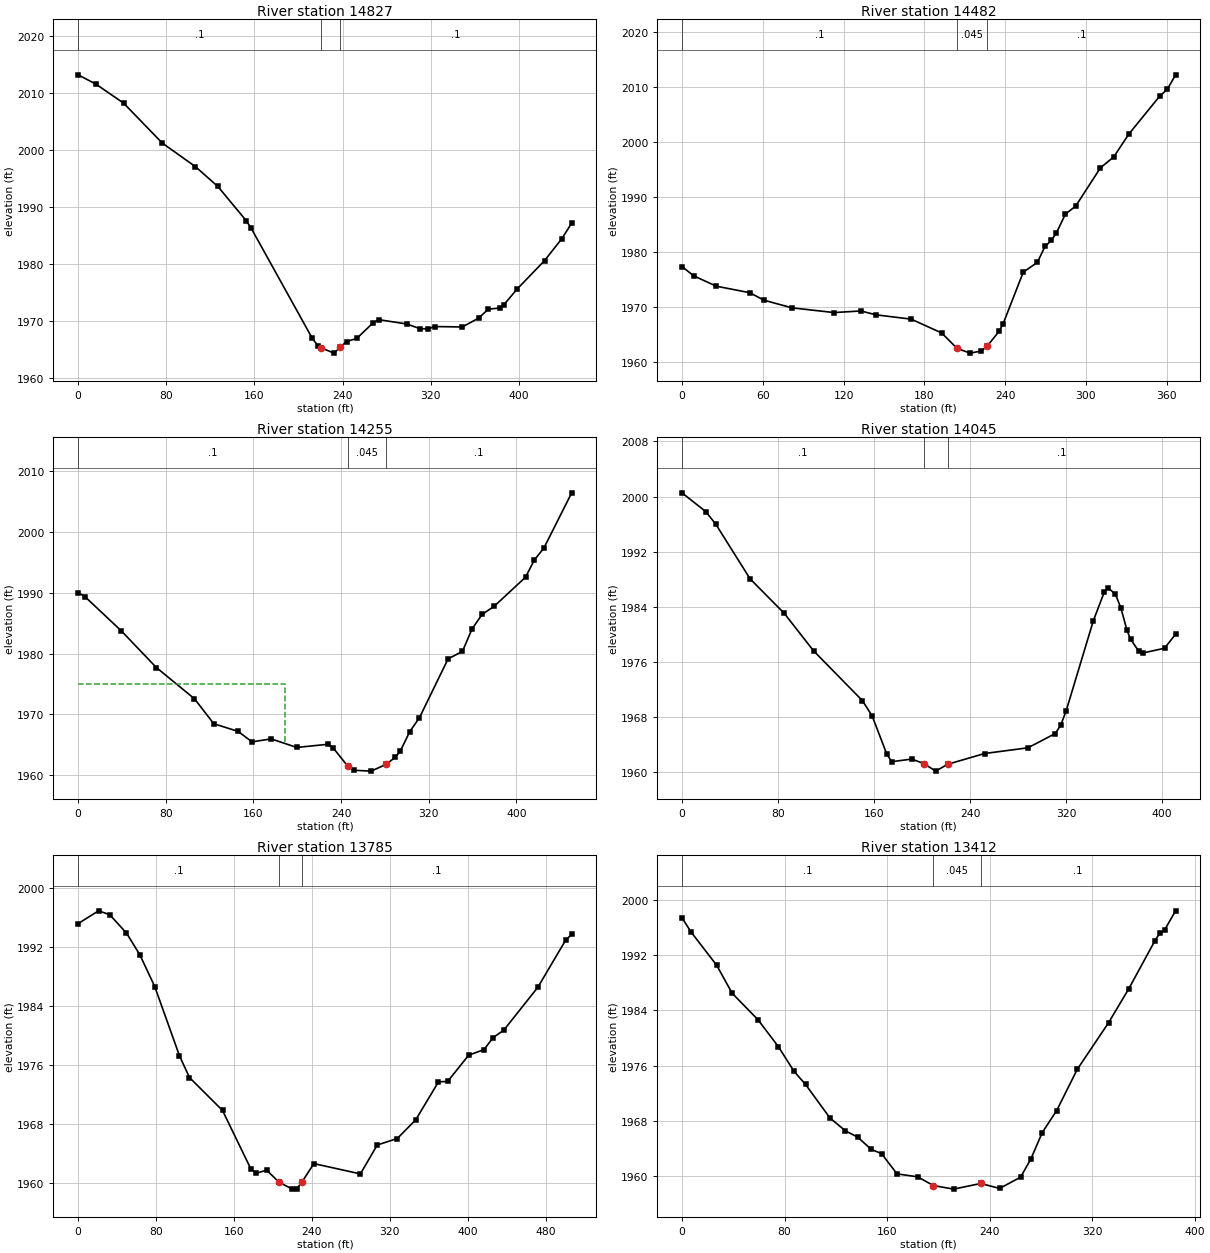
Type RM Length L Ch R = 1 ,14827   ,341.3,345.4,345.6
XS GIS Cut Line= 3
2186144.84601686658817.9434233962185862.29499374658601.389719552
2185784.95438523658551.891730102
#Sta/Elev= 30
       0 2013.14      16 2011.53    41.2 2008.19    76.4 2001.17   106.5 1997.03
   126.8 1993.56   152.5 1987.57   157.1 1986.22   212.5 1966.92   217.9 1965.55
   220.7 1965.25   232.1 1964.34     238 1965.39   243.5 1966.37   252.8 1966.92
   267.9  1969.7     273  1970.2   298.2 1969.45   310.3 1968.62   317.7  1968.6
   323.4    1969   348.6 1968.93   363.3 1970.47   372.2 1972.06   382.3 1972.24
   386.1 1972.78   398.2 1975.56   423.2 1980.57   438.8  1984.4   447.8 1987.14
#Mann= 3 ,-1,0
       0      .1       0   220.7    .045       0     238      .1       0
Bank Sta=220.7,238
XS Rating Curve= 0 ,0
Exp/Cntr=0.3,0.1

Type RM Length L Ch R = 1 ,14482   ,217.9,226.9,234.4
XS GIS Cut Line= 3
2186166.85696302658526.2172650922185916.56493051658317.474007886
2185886.86613684 658289.63138882
#Sta/Elev= 30
       0 1977.38     8.7  1975.7    25.4 1973.82    50.4 1972.63    60.8 1971.28
    81.6 1969.89   112.9 1969.03   132.8 1969.32   144.1 1968.62   170.2 1967.84
   192.9 1965.32   204.3 1962.53     214 1961.67   222.3 1962.06   226.5 1962.89
   235.5 1965.63   238.4 1966.94   253.5 1976.38   263.9 1978.12   269.6 1981.02
   274.3 1982.12   278.1  1983.5   284.8 1986.92   292.3 1988.32   310.8  1995.3
   320.7 1997.29   331.9 2001.43   354.7 2008.27   360.4 2009.53   366.6 2012.17
#Mann= 3 ,-1,0
       0      .1       0   204.3    .045       0   226.5      .1       0
Bank Sta=204.3,226.5
XS Rating Curve= 0 ,0
Exp/Cntr=0.3,0.1

Type RM Length L Ch R = 1 ,14255   ,201.3,210.2,214.8
XS GIS Cut Line= 3
2186290.60193664658506.6243109352186145.20159263 658173.54409026
 2186096.7348113658101.359522312
#Sta/Elev= 30
       0 1990.01     6.1 1989.37    39.4 1983.73    71.4  1977.7   106.2 1972.56
   123.8 1968.46     146  1967.2   158.7 1965.48   176.2 1965.97   199.5 1964.56
   227.8 1965.08   232.9 1964.45     246  1961.5     246 1961.49   252.1 1960.81
   267.3 1960.67   280.9 1961.76   289.6 1962.97     294 1963.97   302.7 1967.18
   311.5 1969.46   337.6 1979.12   350.7 1980.35   359.5 1984.05   368.7 1986.44
   379.6 1987.75   408.3 1992.55   416.3 1995.37     425 1997.33   450.4 2006.41
#Mann= 3 ,-1,0
       0      .1       0     246    .045       0   280.9      .1       0
#XS Ineff= 2 , 0
          189.01 1974.95
Permanent Ineff=
       F       F
Bank Sta=246,280.9
XS Rating Curve= 0 ,0
Exp/Cntr=0.3,0.1

Type RM Length L Ch R = 1 ,14045   ,265.3,259.8,251.1
XS GIS Cut Line= 3
2186420.09055949658468.8259395982186371.62377815658217.211159894
2186297.37679397658081.091688906
#Sta/Elev= 30
       0 2000.54    19.8 1997.81    28.2 1995.97    56.7 1988.05    85.2 1983.03
   109.6 1977.59   150.4 1970.33   158.5  1968.1   170.7 1962.55   174.8 1961.47
   191.4 1961.85   201.5  1961.2   211.4  1960.1   221.41961.099   252.2 1962.66
   288.3 1963.49     311 1965.56   315.5 1966.75   320.1 1968.86   342.8 1981.98
     352 1986.18   355.3 1986.69   361.1 1985.82   365.6 1983.87   370.8 1980.57
   373.8 1979.26   380.4 1977.58   383.9 1977.26   402.1 1977.96   411.3    1980
#Mann= 3 ,-1,0
       0      .1       0   201.5    .045       0   221.4      .1       0
Bank Sta=201.5,221.4
XS Rating Curve= 0 ,0
Exp/Cntr(USF)=0,0
Exp/Cntr=0.3,0.1

Type RM Length L Ch R = 1 ,13785   ,378.5,372.8,348.2
XS GIS Cut Line= 4
2186662.42446617658264.6467331172186482.99425441658075.935648338
2186432.46505685658018.1879939792186287.06471284657930.535304328
#Sta/Elev= 30
       0 1995.22      21 1996.96    32.4 1996.44    49.7 1993.94    63.5 1990.96
    78.7 1986.67   104.1 1977.25   114.4 1974.29   148.3 1969.82   177.4 1961.87
   183.2 1961.29   193.6  1961.7   206.4 1960.06     220 1959.12   224.7  1959.2
   229.7 1960.04   242.1 1962.59   289.9 1961.19   307.2 1965.12   327.8    1966
   346.8 1968.56   370.1 1973.71   379.5 1973.76   401.1 1977.33   416.8 1978.09
   426.2 1979.72   437.2 1980.74   472.1 1986.56   500.9 1993.02   506.9 1993.75
#Mann= 3 ,-1,0
       0      .1       0   206.4    .045       0   229.7      .1       0
Bank Sta=206.4,229.7
XS Rating Curve= 0 ,0
Exp/Cntr(USF)=0,0
Exp/Cntr=0.3,0.1

Type RM Length L Ch R = 1 ,13412   ,227,231.5,237.1
XS GIS Cut Line= 3
2186759.05715311657843.426424743 2186679.6755467657835.624971974
2186375.78779651 657808.85274693
#Sta/Elev= 30
       0 1997.42     6.9 1995.39      27 1990.55    39.1 1986.49    59.2 1982.66
    75.2 1978.74    87.3 1975.19    96.3 1973.29   115.4 1968.42   127.4 1966.57
   136.9 1965.66   147.5 1963.89   155.6 1963.26   167.6 1960.34   183.7 1959.91
     196 1958.65   211.8 1958.13   232.9 1958.95   247.6 1958.23     264 1959.87
     272  1962.5   280.8 1966.31   292.1 1969.51   308.1 1975.46   332.5 1982.21
   348.3 1987.14   368.4    1994   372.4 1995.17   376.4 1995.71   384.8 1998.42
#Mann= 3 ,-1,0
       0      .1       0     196    .045       0   232.9      .1       0
Bank Sta=196,232.9
XS Rating Curve= 0 ,0
Exp/Cntr(USF)=0,0
Exp/Cntr=0.3,0.1

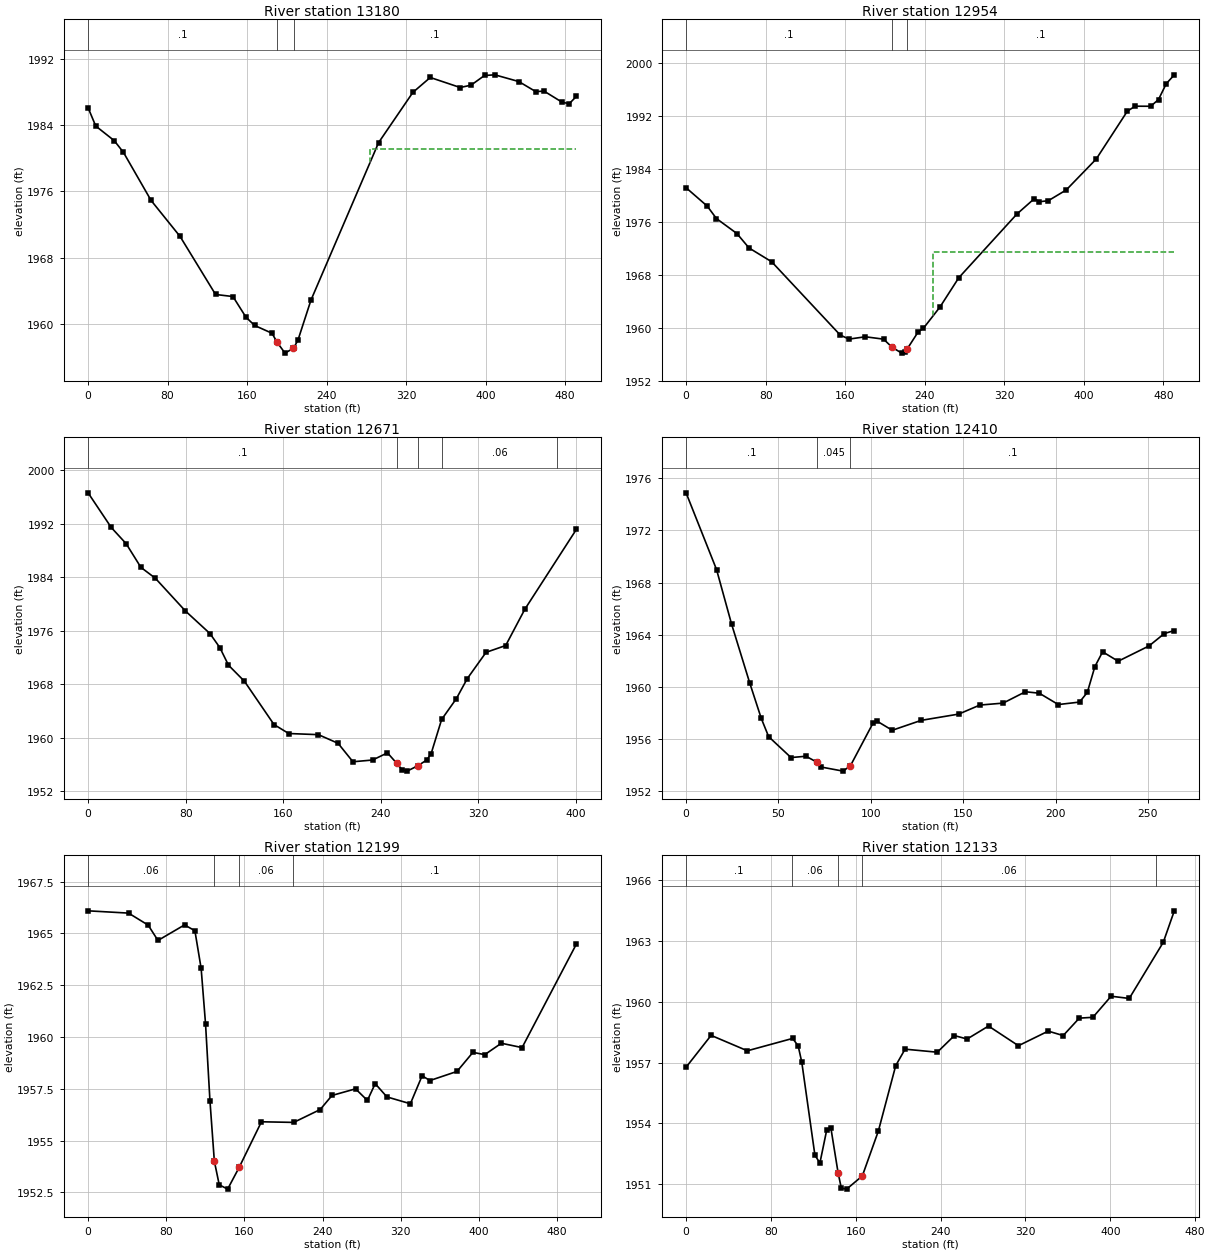
Type RM Length L Ch R = 1 ,13180   ,214.6,226.7,233.9
XS GIS Cut Line= 4
2186762.81590668657689.3175282142186654.85008445657625.579337159
2186522.44805505657567.6534492982186313.61085628 657493.88468058
#Sta/Elev= 30
       0 1986.11     7.7  1983.9    26.3 1982.14    35.6 1980.72    63.4 1974.92
    92.6 1970.57   128.3 1963.57   145.8 1963.32   158.9 1960.83   167.6 1959.83
   185.1 1958.89   190.31957.789   198.2 1956.49   206.7 1957.08   206.9  1957.1
   211.3 1958.08   224.3 1962.88   292.4  1981.9   326.9 1987.96   344.4 1989.76
   374.5 1988.55   385.4 1988.83     399    1990   409.4 1990.08   433.5 1989.27
   450.5 1988.06     459 1988.11   477.4 1986.75   484.4 1986.61   491.4 1987.47
#Mann= 3 ,-1,0
       0      .1       0   190.3    .045       0   206.9      .1       0
#XS Ineff= 2 , 0
                          283.66         1981.13
Permanent Ineff=
       F       T
Bank Sta=190.3,206.7
XS Rating Curve= 0 ,0
Exp/Cntr(USF)=0,0
Exp/Cntr=0.3,0.1

Type RM Length L Ch R = 1 ,12954   ,278.2,282.8,286.2
XS GIS Cut Line= 4
 2186797.6773009657592.7714421292186715.21030112657491.870642405
2186661.84930127657368.6552427432186467.32240235657253.080139192
#Sta/Elev= 30
       0 1981.16    21.3 1978.38    30.5 1976.51    51.1 1974.24    63.3 1972.06
    86.1 1969.97     155  1958.9   163.8 1958.29   180.3 1958.64   198.6 1958.28
   207.11957.057   216.8 1956.17   220.4 1956.28   222.61956.869   233.5 1959.41
   238.6 1959.92   255.3 1963.14   274.2 1967.56   332.6 1977.18   350.3 1979.53
   354.9 1979.04   364.2  1979.2   382.2 1980.82   412.4  1985.5   443.7 1992.73
   451.5 1993.48   467.2 1993.47     475 1994.49   482.8 1996.88   490.9 1998.22
#Mann= 3 ,-1,0
       0      .1       0   207.1    .045       0   222.6      .1       0
#XS Ineff= 2 , 0
                          248.45         1971.42
Permanent Ineff=
       F       F
Bank Sta=207.1,222.6
XS Rating Curve= 0 ,0
Exp/Cntr(USF)=0,0
Exp/Cntr=0.3,0.1

Type RM Length L Ch R = 1 ,12671   ,258.5,260.5,259.5
XS GIS Cut Line= 3
2186951.68366861657524.0314786922186899.71077969 657163.00551814
2186895.99843048657127.738200657
#Sta/Elev= 30
       0  1996.6      19 1991.42    31.2    1989    43.3 1985.46    55.1 1983.84
    79.8 1978.94    99.9 1975.57     108 1973.47   115.1 1970.84   128.2 1968.43
   152.4 1961.97   164.5 1960.63   188.8 1960.46   204.9 1959.17   217.1 1956.41
   233.2 1956.67   245.4 1957.74   252.9  1956.2   257.5  1955.2   261.5 1955.01
   270.6 1955.84   277.7 1956.69   281.2 1957.63   289.8 1962.73   301.9 1965.85
   310.8 1968.83   326.2 1972.76   342.3 1973.78     358  1979.2   400.2 1991.12
#Mann= 5 ,-1,0
       0      .1       0   252.9    .045       0   270.6      .1       0
     290     .06       0  384.75      .1       0
Bank Sta=252.9,270.6
XS Rating Curve= 0 ,0
Exp/Cntr(USF)=0,0
Exp/Cntr=0.3,0.1

Type RM Length L Ch R = 1 ,12410   ,246.8,211.2,193.1
XS GIS Cut Line= 4
2187174.47772945657369.6010023262187162.52453445657269.089873067
 2187083.9933294657268.4918300822187003.06779483657244.134097702
#Sta/Elev= 30
       0 1974.88    16.5    1969    24.6 1964.84    34.4 1960.34    40.7  1957.6
    44.7  1956.2    56.8  1954.6    64.9  1954.7    70.9 1954.24    72.9 1953.88
      85 1953.56      89 1953.98   101.2 1957.24   103.6 1957.37   111.6 1956.69
   127.3 1957.45   147.6 1957.93     159 1958.62   171.6 1958.77   183.7 1959.64
   191.2 1959.53   201.5 1958.66     213 1958.85   217.2 1959.59   221.3 1961.57
   225.5  1962.7   233.9 1961.98   250.6 1963.15   258.9  1964.1   264.3 1964.33
#Mann= 3 ,-1,0
       0      .1       0    70.9    .045       0      89      .1       0
Bank Sta=70.9,89
XS Rating Curve= 0 ,0
Exp/Cntr(USF)=0,0
Exp/Cntr=0.3,0.1

Type RM Length L Ch R = 1 ,12199   ,59.4,66.2,71.8
XS GIS Cut Line= 6
2187465.54909391657136.4782508112187377.84484385657201.629979425
2187264.24695806657260.934758035 2187212.4596866657266.781708039
2187097.19124367657265.1111508952187007.81643647 657233.37056516
#Sta/Elev= 30
       0 1966.09    41.4 1965.98    61.5  1965.4    71.5 1964.66    98.7 1965.41
   109.3 1965.13   115.7 1963.31   120.2 1960.63   124.7 1956.93   129.2 1954.01
   134.2 1952.87   142.8 1952.66   154.6 1953.71   177.4 1955.91   210.4 1955.88
   237.5  1956.5   249.6 1957.18   273.7  1957.5   285.8 1956.94   293.8 1957.75
   305.8 1957.11   329.8 1956.78   341.8 1958.13   349.8  1957.9   377.5 1958.34
   393.8 1959.26   405.9 1959.15   422.9  1959.7   444.1 1959.49   499.6 1964.48
#Mann= 4 ,-1,0
       0     .06       0   129.2    .045       0   154.6     .06       0
  209.26      .1       0
Bank Sta=129.2,154.6
XS Rating Curve= 0 ,0
Exp/Cntr(USF)=0,0
Exp/Cntr=0.3,0.1

Type RM Length L Ch R = 1 ,12133   ,166.5,183.1,205
XS GIS Cut Line= 5
2187432.13795103657088.0320936372187347.77481526657154.019100823
2187257.56472949 657220.841386582187124.75543654657235.876400876
2187024.52200791657197.453586565
#Sta/Elev= 30
       0 1956.77    23.6 1958.34    57.8 1957.58   100.5 1958.19   105.7 1957.82
   109.1 1957.02   121.5 1952.43   126.2 1952.05   132.6 1953.67   136.5 1953.79
   143.4 1951.55   146.4 1950.81   151.4 1950.76   166.2 1951.41   181.3 1953.62
   197.7 1956.85   206.5 1957.66   236.9 1957.51     253 1958.33     265 1958.16
   285.2  1958.8   313.4 1957.83   341.5 1958.55   355.6 1958.33   370.8 1959.19
   383.6 1959.23   400.8 1960.27   417.9 1960.16     450 1962.93   460.4 1964.48
#Mann= 5 ,-1,0
       0      .1       0     100     .06       0   143.4    .045       0
   166.2     .06       0  443.03      .1       0
Bank Sta=143.4,166.2
XS Rating Curve= 0 ,0
Exp/Cntr(USF)=0,0
Exp/Cntr=0.3,0.1

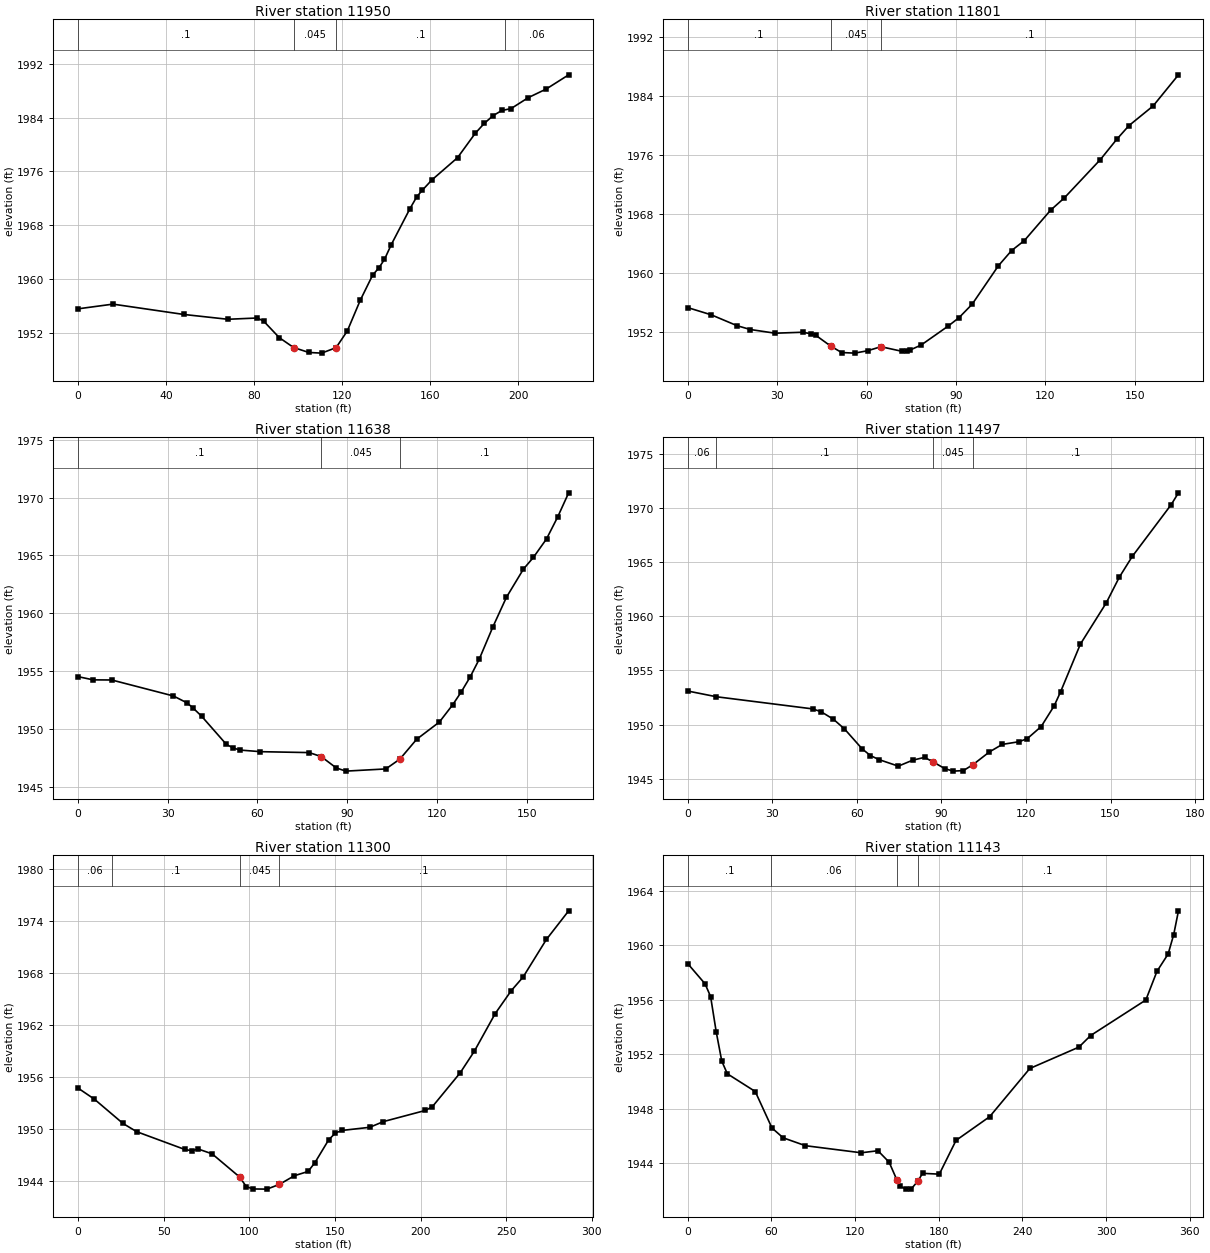
Type RM Length L Ch R = 1 ,11950   ,144.2,148.7,153.9
XS GIS Cut Line= 4
2187307.96032643657133.9333827112187231.11469781657126.415875563
2187178.49214778657070.4522112412187109.99930488657062.099425521
#Sta/Elev= 30
       0 1955.58    15.9 1956.28      48 1954.75    68.1 1954.03    81.5 1954.22
    84.4 1953.75    91.5  1951.3      981949.834   104.9  1949.1   110.7    1949
   117.3 1949.81   122.4 1952.29   128.3 1956.86   133.9 1960.58   136.8 1961.69
   139.3 1962.93   142.4 1965.13   150.9 1970.48     154 1972.24   156.4 1973.17
   160.8 1974.72   172.5 1978.04   180.5 1981.64   184.6 1983.12   188.6 1984.27
   192.6 1985.05   196.8 1985.33   204.7 1986.97   212.8 1988.24     223 1990.35
#Mann= 4 ,-1,0
       0      .1       0      98    .045       0   117.3      .1       0
  194.03     .06       0
Bank Sta=98,117.3
XS Rating Curve= 0 ,0
Exp/Cntr(USF)=0,0
Exp/Cntr=0.3,0.1

Type RM Length L Ch R = 1 ,11801   ,163.9,163.6,165.1
XS GIS Cut Line= 3
2187363.63780186657088.3766053612187305.18166628656956.850300303
2187296.65681317656937.973839855
#Sta/Elev= 30
       0 1955.35     7.9 1954.37    16.6 1952.89      21 1952.38    29.3 1951.88
    38.5 1952.01    41.4  1951.8    42.9 1951.61    47.9 1950.15    51.6 1949.26
      56 1949.18    60.4 1949.51    64.8 1950.05    71.7 1949.44    73.5 1949.46
    74.7 1949.62    78.3 1950.28    87.3 1952.83      91 1953.99    95.4 1955.81
   104.2 1961.02   108.6 1963.07   112.9 1964.43   121.7 1968.55   126.3 1970.21
   138.4 1975.41   143.9 1978.16     148 1980.02   156.1 1982.68   164.6  1986.9
#Mann= 3 ,-1,0
       0      .1       0    47.9    .045       0    64.8      .1       0
Bank Sta=47.9,64.8
XS Rating Curve= 0 ,0
Exp/Cntr(USF)=0,0
Exp/Cntr=0.3,0.1

Type RM Length L Ch R = 1 ,11638   ,140.7,140.4,138.7
XS GIS Cut Line= 3
2187510.38705889657022.0045347532187468.37171144656933.711413303
2187438.53472557656874.646359643
#Sta/Elev= 30
       0 1954.54     5.1 1954.26    11.3 1954.25    31.9 1952.87    36.4 1952.28
    38.3 1951.87    41.3 1951.13    49.6 1948.69    51.7  1948.4    54.1  1948.2
      61 1948.06    77.3 1947.98    81.31947.636    86.3 1946.66    89.5 1946.38
   102.9 1946.57   107.6 1947.42   113.2 1949.13   120.8 1950.62   125.3 1952.13
   128.1 1953.22   131.1 1954.52   134.1 1956.04   138.7 1958.85   143.2 1961.39
   148.9 1963.83   152.2 1964.83   156.6 1966.43   160.3 1968.31     164 1970.41
#Mann= 3 ,-1,0
       0      .1       0    81.3    .045       0   107.6      .1       0
Bank Sta=81.3,107.6
XS Rating Curve= 0 ,0
Exp/Cntr(USF)=0,0
Exp/Cntr=0.3,0.1

Type RM Length L Ch R = 1 ,11497   ,189,197.3,202.4
XS GIS Cut Line= 2
2187631.78394071656950.0513183452187545.33260851656798.949424675
#Sta/Elev= 30
       0  1953.1    10.2 1952.57    44.3 1951.45    47.3 1951.19    51.7 1950.49
    55.6  1949.6    61.9 1947.75    64.8 1947.14    67.8 1946.77    74.7 1946.16
    79.8 1946.71      84 1946.97      87 1946.56    91.2 1945.93    94.2  1945.7
    97.8 1945.75   101.21946.298     107 1947.47   111.6 1948.17   117.6 1948.42
   120.5 1948.71   125.4 1949.82     130 1951.73   132.3 1953.04   139.3 1957.43
   148.5 1961.25   153.1 1963.61   157.7 1965.53   171.5 1970.31   174.1 1971.41
#Mann= 4 ,-1,0
       0     .06       0      10      .1       0      87    .045       0
   101.2      .1       0
Bank Sta=87,101.2
XS Rating Curve= 0 ,0
Exp/Cntr(USF)=0,0
Exp/Cntr=0.3,0.1

Type RM Length L Ch R = 1 ,11300   ,156.9,157,157
XS GIS Cut Line= 3
2187771.46909056656959.5139492642187771.46909056656781.509536157
2187751.18481151656675.073362256
#Sta/Elev= 30
       0  1954.7     9.6 1953.41    26.3  1950.6    34.3 1949.65    62.3  1947.6
    66.3 1947.45    70.3 1947.64    78.3 1947.09    94.3 1944.42    98.3 1943.29
   102.3 1943.03   110.3 1943.01   117.6 1943.56   126.3 1944.56   134.3 1945.05
   138.3 1946.07   146.3  1948.7   150.3 1949.51   154.3  1949.8   170.3 1950.16
   178.3 1950.82   202.8 1952.11   206.8 1952.53   223.1 1956.46   231.3 1958.94
   243.5  1963.3   252.9 1965.96   259.8 1967.53   273.4 1971.88   286.4 1975.19
#Mann= 4 ,-1,0
       0     .06       0      20      .1       0    94.3    .045       0
   117.6      .1       0
Bank Sta=94.3,117.6
XS Rating Curve= 0 ,0
Exp/Cntr=0.3,0.1

Type RM Length L Ch R = 1 ,11143   ,177.7,181.6,183.4
XS GIS Cut Line= 3
2187924.27414297657001.5916065192187929.16609114 656748.12725194
2187927.69674816656649.747482269
#Sta/Elev= 30
       0 1958.66    12.4 1957.18    16.4 1956.24    20.4 1953.66    24.4  1951.5
    28.4 1950.57    48.4 1949.27    60.4 1946.59    68.4 1945.87    84.4 1945.29
   124.4 1944.77   136.4 1944.92   144.4 1944.08     1501942.771   152.4 1942.31
   156.4  1942.1   160.4 1942.13   164.91942.674   168.4 1943.26   180.4  1943.2
   192.4 1945.68   216.5 1947.42   245.3 1950.96   280.5 1952.53   288.9 1953.38
   328.5 1955.99   336.5  1958.1   344.5 1959.37   348.5  1960.8   351.9 1962.54
#Mann= 4 ,-1,0
       0      .1       0      60     .06       0     150    .045       0
   164.9      .1       0
Bank Sta=150,164.9
XS Rating Curve= 0 ,0
Exp/Cntr=0.3,0.1