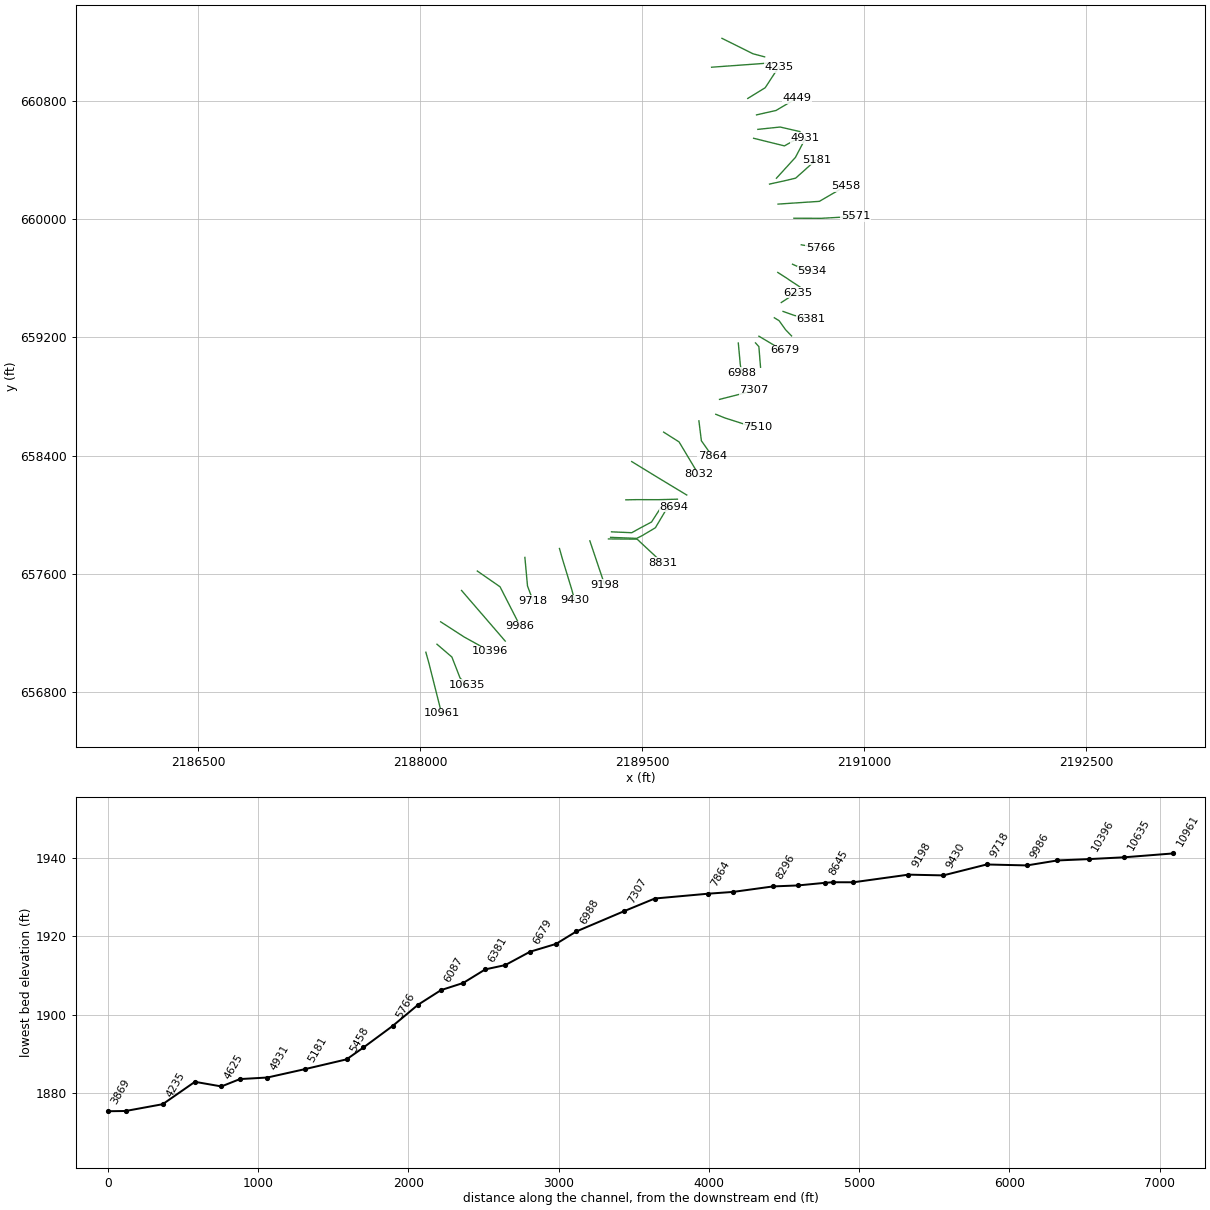
HEC-RAS study BIGRN.prj: BIGRN

--- BIGRN.g01 (geometry) --- (continued)

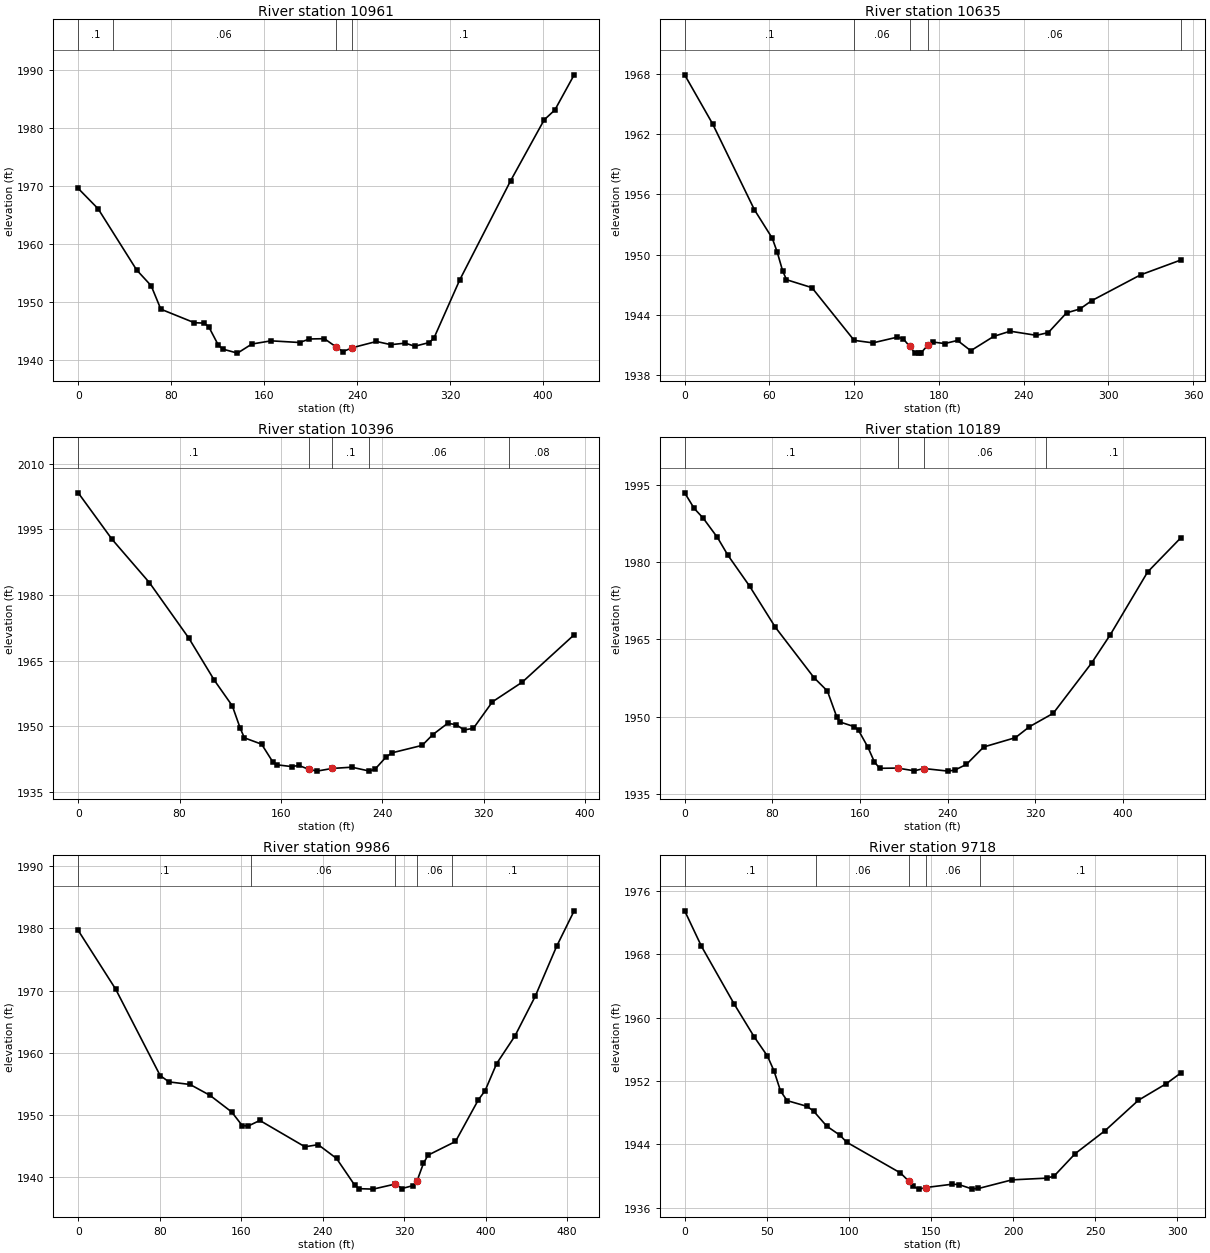
Type RM Length L Ch R = 1 ,10961   ,320.1,326.8,325.7
XS GIS Cut Line= 3
 2188037.9984171657069.6036289052188057.92351066656998.618480756
2188144.23562977656656.154266246
#Sta/Elev= 30
       0 1969.59    17.1 1966.09    50.3 1955.53    62.8 1952.81    71.1 1948.77
     100 1946.43   108.2 1946.37   112.3 1945.76   120.6 1942.57   124.7 1941.87
   137.1 1941.19   149.5 1942.76     166 1943.31   190.7 1943.02     199 1943.63
   211.9 1943.68   221.5 1942.33   227.8 1941.45   236.1 1942.13   256.7  1943.2
   269.1 1942.65   281.5 1942.91   289.7 1942.38   302.1 1943.01   306.2 1943.78
   328.4 1953.81   372.2 1970.91   401.1 1981.42   410.3 1983.12   426.9 1989.18
#Mann= 4 ,-1,0
       0      .1       0      30     .06       0   221.5    .045       0
   236.1      .1       0
Bank Sta=221.5,236.1
XS Rating Curve= 0 ,0
Exp/Cntr=0.3,0.1

Type RM Length L Ch R = 1 ,10635   ,227.7,238.2,241.6
XS GIS Cut Line= 4
2188113.17348858657123.8967360842188214.24219579657037.027764598
2188269.37058154656895.0304073622188316.98146014656849.925364476
#Sta/Elev= 30
       0 1967.87    19.8 1962.99    49.4 1954.45      62 1951.63    65.5 1950.26
    69.3 1948.41    72.1  1947.5    90.1 1946.71     120 1941.47   133.3 1941.22
   150.3 1941.78   154.6 1941.65   159.4 1940.86   163.1 1940.22   165.6  1940.2
   167.4 1940.23   172.51941.035     176  1941.3   184.1 1941.15   193.2 1941.46
   202.6 1940.44   218.9 1941.87   230.5 1942.38     249 1941.97   257.5 1942.24
   270.4  1944.2   279.9 1944.59   288.3 1945.42   322.8 1947.98   351.2 1949.45
#Mann= 5 ,-1,0
       0      .1       0     120     .06       0   159.4    .045       0
   172.5     .06       0  351.18      .1       0
Bank Sta=159.4,172.5
XS Rating Curve= 0 ,0
Exp/Cntr(USF)=0,0
Exp/Cntr=0.3,0.1

Type RM Length L Ch R = 1 ,10396   ,209.8,207.6,197.8
XS GIS Cut Line= 3
2188138.02789569657275.695153545     2188297.267      657172.796
2188473.74342599657075.182464799
#Sta/Elev= 30
       0 2003.35    26.7 1992.72    56.2 1982.81    87.3 1970.12   107.5 1960.46
   121.6 1954.64   127.8 1949.55   131.1 1947.34   144.7 1945.89   153.8 1941.71
   156.7 1941.18   168.3 1940.77   174.1 1941.03   181.81940.157   188.3 1939.73
   200.3 1940.34   215.8 1940.63   229.5 1939.76   234.1 1940.14   243.2 1943.05
   247.8 1943.93   271.4 1945.62   279.7 1948.06   291.5 1950.66   298.1 1950.36
   304.5 1949.14   311.8 1949.52   326.8 1955.57   350.4 1960.08   391.3  1970.9
#Mann= 5 ,-1,0
       0      .1       0   181.8    .045       0   200.3      .1       0
  229.59     .06       0  339.59     .08       0
Bank Sta=181.8,200.3
XS Rating Curve= 0 ,0
Exp/Cntr=0.3,0.1

Type RM Length L Ch R = 1 ,10189   ,204.9,202.3,195.7
XS GIS Cut Line= 2
2188279.16399533 657487.799306762188574.64810651657145.163475706
#Sta/Elev= 30
       0 1993.53     8.7 1990.49    16.8 1988.63    29.9 1984.84    39.4  1981.4
    59.3 1975.35    82.7 1967.38   117.9 1957.59   130.2 1954.97   138.7 1949.95
   141.5 1948.96   154.7 1948.04   158.6 1947.32   167.1 1944.06     173 1941.21
   177.8 1939.94   194.21939.983   209.5 1939.45   218.1  1939.9   240.4 1939.39
   246.5  1939.6     257  1940.7   272.8 1944.09   301.7  1945.9   314.5 1948.03
   336.2 1950.64   371.3 1960.45   388.3 1965.94   422.3 1978.13   452.4 1984.74
#Mann= 4 ,-1,0
       0      .1       0   194.2    .045       0   218.1     .06       0
     330      .1       0
Bank Sta=194.2,218.1
XS Rating Curve= 0 ,0
Exp/Cntr=0.3,0.1

Type RM Length L Ch R = 1 ,9986    ,266.1,268.2,262.8
XS GIS Cut Line= 3
2188385.96393257657619.0845065912188539.60672303657512.501929598
2188675.99121451657245.377779864
#Sta/Elev= 30
       0 1979.67    36.8 1970.23    80.5 1956.35    89.2 1955.34   109.8 1954.93
   129.3 1953.19   150.7 1950.51     161 1948.33   166.8 1948.25   178.3 1949.15
   222.6 1944.92   235.6 1945.26   253.6 1943.05   271.6 1938.72   276.1 1938.19
   289.5 1938.12   311.4 1938.94   317.7 1938.21     329  1938.7   332.6 1939.42
   338.9 1942.24   343.4 1943.57   370.4 1945.77   392.8 1952.45   399.4 1953.91
   410.8 1958.28   428.8 1962.73   448.6 1969.06   469.7 1977.12   486.9 1982.82
#Mann= 5 ,-1,0
       0      .1       0     170     .06       0   311.4    .045       0
   332.6     .06       0  366.99      .1       0
Bank Sta=311.4,332.6
XS Rating Curve= 0 ,0
Exp/Cntr=0.3,0.1

Type RM Length L Ch R = 1 ,9718    ,283.9,288.6,289.6
XS GIS Cut Line= 3
2188707.52519043657711.3642934782188725.24996368657517.363044645
2188763.30154307657417.129616008
#Sta/Elev= 30
       0 1973.49    10.2 1969.02    30.3 1961.67    42.4 1957.56    50.4 1955.16
    54.4 1953.28    58.4 1950.73    62.4 1949.53    74.5 1948.81    78.5 1948.21
    86.5 1946.31    94.6 1945.16    98.6 1944.29   131.4  1940.4   136.5 1939.36
   138.8 1938.72   142.8 1938.36   146.8 1938.56   162.9 1938.98   166.9 1938.94
   174.9 1938.39   178.9 1938.44   199.3 1939.53   220.7 1939.75     225 1940.02
   237.8 1942.84   256.1 1945.76   276.3 1949.58   293.4 1951.69     302    1953
#Mann= 5 ,-1,0
       0      .1       0      80     .06       0   136.5    .045       0
   146.8     .06       0     180      .1       0
Bank Sta=136.5,146.8
XS Rating Curve= 0 ,0
Exp/Cntr=0.3,0.1

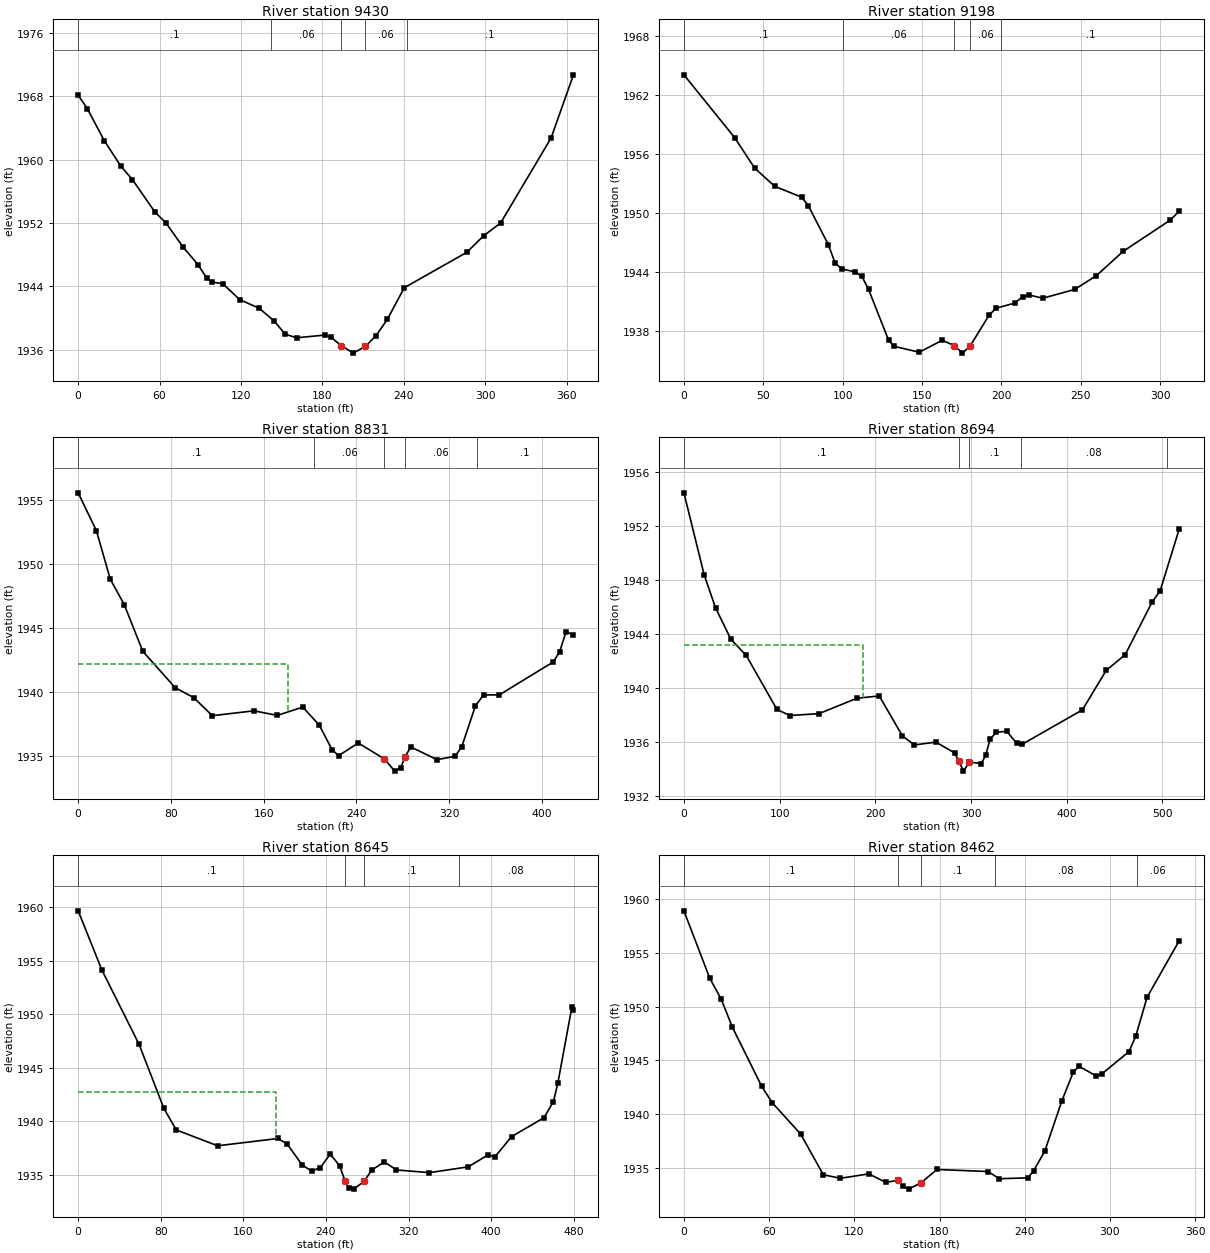
Type RM Length L Ch R = 1 ,9430    ,228.1,231.6,228.6
XS GIS Cut Line= 4
2188941.38684632657771.6208668572188960.87667966657702.014319193
2189024.91470352657492.2665888962189043.95513382657421.244357994
#Sta/Elev= 30
       0 1968.13     6.7 1966.45    19.2 1962.41    31.6 1959.14      40 1957.48
    56.5  1953.4    64.8 1951.99    77.3 1948.97    88.4 1946.73    94.8 1945.04
    98.3 1944.56   106.6 1944.33   119.2 1942.31   133.3 1941.25   144.3 1939.66
   152.6 1937.96     161 1937.51   181.9 1937.85   186.1 1937.61   194.1  1936.5
   202.8 1935.57   211.81936.432   219.5 1937.76   227.9 1939.83   240.4 1943.83
   286.5  1948.3   298.9 1950.39   311.4    1952   348.6 1962.73   365.1 1970.71
#Mann= 5 ,-1,0
       0      .1       0  142.28     .06       0   194.1    .045       0
   211.8     .06       0  242.28      .1       0
Bank Sta=194.1,211.8
XS Rating Curve= 0 ,0
Exp/Cntr=0.3,0.1

Type RM Length L Ch R = 1 ,9198    ,356.7,366.6,370.7
XS GIS Cut Line= 2
2189146.71747229657823.3889356872189246.17409185657527.725379565
#Sta/Elev= 30
       0 1964.04    31.9 1957.67    44.5 1954.57    57.2 1952.71    74.1 1951.61
    78.3 1950.76      91 1946.77    95.2 1944.92    99.4 1944.32   107.8 1944.01
   112.1 1943.55   116.3 1942.23   128.9 1937.07   132.4 1936.45   148.2 1935.85
   162.7 1937.07   170.3 1936.52   175.4 1935.76   180.2 1936.47   192.2 1939.62
   196.5 1940.32   208.2 1940.84   213.3 1941.48   217.6 1941.66     226 1941.34
   246.1 1942.23   259.8 1943.64   276.6  1946.1   306.2 1949.27   311.9 1950.18
#Mann= 5 ,-1,0
       0      .1       0     100     .06       0   170.3    .045       0
   180.2     .06       0     200      .1       0
Bank Sta=170.3,180.2
XS Rating Curve= 0 ,0
Exp/Cntr=0.3,0.1

Type RM Length L Ch R = 1 ,8831    ,120.3,137.8,150
XS GIS Cut Line= 3
2189272.48428199657836.4560387152189466.20919376657834.835543078
2189636.85660601657675.464391545
#Sta/Elev= 30
       0 1955.59    15.7 1952.63    27.7 1948.83    39.7 1946.85    55.7 1943.19
    83.7 1940.34    99.7 1939.56   115.7 1938.15   151.7 1938.53   171.7 1938.17
   193.7 1938.82   207.9 1937.42   218.9  1935.5   224.6 1935.02   241.6 1936.01
   264.2 1934.76     273 1933.81   278.4 1934.09   281.71934.909   286.9  1935.7
   309.5 1934.71   325.1 1934.97   330.9 1935.73   342.7 1938.93   349.7 1939.77
   363.3 1939.78   409.9 1942.36   415.3 1943.16   420.8  1944.7   427.2  1944.5
#Mann= 5 ,-1,0
       0      .1       0  203.73     .06       0   264.2    .045       0
   281.7     .06       0  343.73      .1       0
#XS Ineff= 2 , 0
          181.41 1942.21
Permanent Ineff=
       T       F
Bank Sta=264.2,281.7
XS Rating Curve= 0 ,0
Exp/Cntr=0.3,0.1

Type RM Length L Ch R = 1 ,8694    ,49,48.3,48.2
XS GIS Cut Line= 6
2189287.08930393657847.145696432 2189463.2021909657840.097798081
2189498.02752022 657857.212660012189589.83406538657911.998399531
 2189657.8938753658026.5533835712189713.49789171658054.619604408
#Sta/Elev= 30
       0 1954.44    21.1 1948.38    33.1 1945.91    49.1 1943.59    65.1 1942.39
    97.2 1938.39   110.7 1937.94   141.2 1938.08   180.8 1939.22   204.1 1939.39
   228.3 1936.43   240.8 1935.76   263.3 1935.97   282.8 1935.17   287.4 1934.54
   292.1 1933.82   298.3 1934.49   310.7 1934.38   315.4 1935.01     320 1936.21
   326.6  1936.7   337.3 1936.77   347.9 1935.87   353.7 1935.82   416.4 1938.36
   441.3 1941.29     461 1942.44   489.1 1946.33   497.6 1947.18   517.5 1951.75
#Mann= 5 ,-1,0
       0      .1       0   287.4    .045       0   298.3      .1       0
  351.97     .08       0  505.22     .06       0
#XS Ineff= 2 , 0
          186.93 1943.16
Permanent Ineff=
       T       F
Bank Sta=287.4,298.3
XS Rating Curve= 0 ,0
Exp/Cntr=0.3,0.1

Type RM Length L Ch R = 1 ,8645    ,187.3,183.6,173.4
XS GIS Cut Line= 6
 2189293.2400005657884.3117768772189430.12515945657878.437084535
2189475.98195305657903.9966088382189563.65663553657950.813209314
2189626.10835157658047.3783818722189693.59118781658081.806810214
#Sta/Elev= 30
       0 1959.68      23 1954.14      59  1947.2      83 1941.22      95 1939.21
   135.1 1937.73   193.5 1938.41   202.4  1937.9   216.9 1935.94     226 1935.37
   234.5 1935.68   244.1 1936.95   253.2 1935.87   258.5 1934.44   262.3 1933.77
   266.8 1933.68   276.9  1934.4   284.4 1935.47   296.5 1936.22   308.3 1935.47
   340.2 1935.22   377.8 1935.76   396.5 1936.85   403.9 1936.72   419.7 1938.58
   451.1 1940.35   460.3 1941.85   464.6 1943.59   478.1 1950.65   479.7 1950.38
#Mann= 4 ,-1,0
       0      .1       0   258.5    .045       0   276.9      .1       0
   368.9     .08       0
#XS Ineff= 2 , 0
          191.83 1942.78
Permanent Ineff=
       T       F
Bank Sta=258.5,276.9
XS Rating Curve= 0 ,0
Exp/Cntr=0.3,0.1

Type RM Length L Ch R = 1 ,8462    ,173,165.3,158.7
XS GIS Cut Line= 4
2189390.01093273658100.7222784812189461.17892231658102.185018316
2189609.27514957658101.9082069982189738.74332822658105.249321286
#Sta/Elev= 30
       0 1958.93    18.2 1952.65    26.2 1950.72    34.2 1948.07    54.8 1942.57
    62.2 1941.05    82.2 1938.13    98.2 1934.34   110.2 1934.01   130.2 1934.42
   142.2 1933.63     151 1933.83   154.2 1933.27   158.2    1933     167 1933.59
   178.2 1934.83   214.2 1934.64   222.2 1933.97   242.2 1934.05   246.2 1934.68
   254.2 1936.56   266.2 1941.23   274.2  1943.9   278.2 1944.45   290.2 1943.56
   294.2 1943.72   313.4 1945.81   318.2 1947.24   326.2 1950.88   348.8 1956.14
#Mann= 5 ,-1,0
       0      .1       0     151    .045       0     167      .1       0
  219.28     .08       0  319.28     .06       0
Bank Sta=151,167
XS Rating Curve= 0 ,0
Exp/Cntr=0.3,0.1

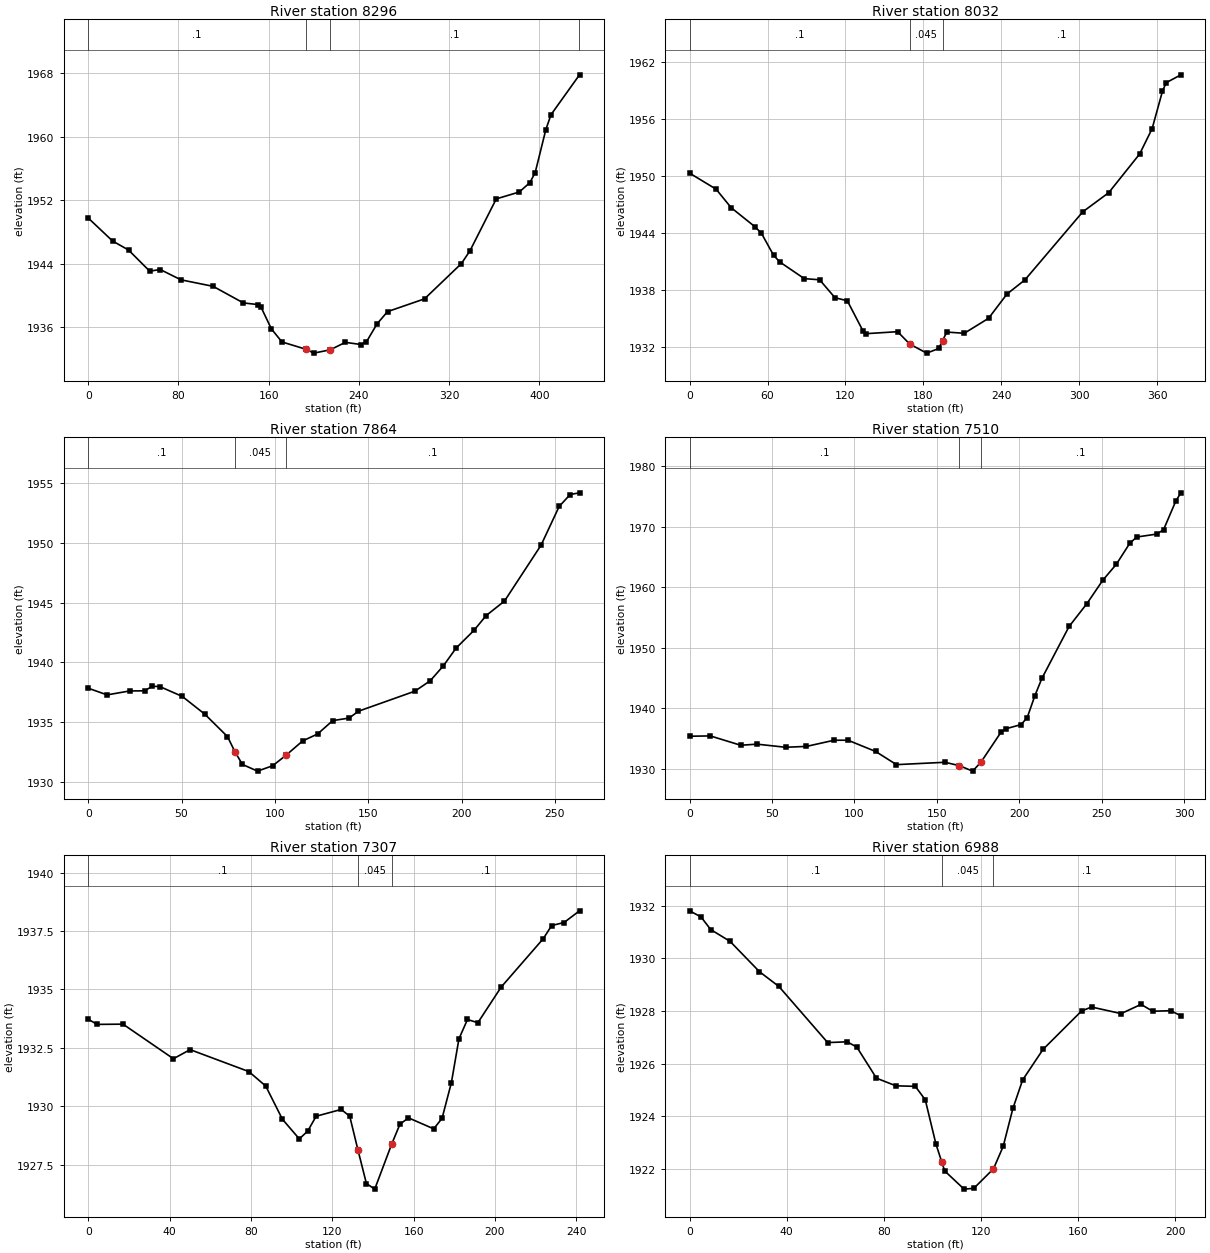
Type RM Length L Ch R = 1 ,8296    ,271.7,264.7,255.7
XS GIS Cut Line= 3
2189429.72938309658359.754015758     2189606.205       658251.69
2189801.75645286658133.425760383
#Sta/Elev= 30
       0 1949.78    21.6 1946.88    35.7 1945.75    54.5 1943.08    63.8 1943.29
    82.2 1941.99   110.7 1941.17   137.5 1939.08   150.5 1938.87     153  1938.6
   162.3 1935.82   171.7 1934.16   193.2 1933.23   199.9 1932.75   214.51933.166
   227.9 1934.11     242 1933.83   246.6 1934.17     256 1936.43   265.3 1937.98
   298.1 1939.59   330.8 1944.04   338.4 1945.65   361.7 1952.19   382.1 1953.06
   391.5 1954.24   396.2  1955.5   405.6  1960.9   410.2  1962.8   435.5 1967.83
#Mann= 4 ,-1,0
       0      .1       0   193.2    .045       0   214.5      .1       0
  435.47     .06       0
Bank Sta=193.2,214.5
XS Rating Curve= 0 ,0
Exp/Cntr=0.3,0.1

Type RM Length L Ch R = 1 ,8032    ,173.5,167.1,156.7
XS GIS Cut Line= 3
2189645.62259875658558.7842033292189749.77461822658492.786884061
2189880.73804864658274.170763988
#Sta/Elev= 30
       0 1950.32    20.4 1948.63      32 1946.68    50.4 1944.66    55.3 1943.98
    64.6 1941.68    69.3 1940.97    88.3  1939.2   100.1 1939.08   111.9 1937.19
   121.4 1936.87   133.5 1933.68   135.8  1933.4   160.1 1933.61   169.5  1932.3
   182.5 1931.35   191.8 1931.84   194.7 1932.68     198 1933.57   211.4 1933.44
   230.1 1935.02   244.3 1937.58   258.1 1939.07   302.6 1946.24   322.6 1948.26
   346.4 1952.34     356 1955.01   363.9 1958.93   366.8 1959.85   378.1 1960.68
#Mann= 3 ,-1,0
       0      .1       0   169.5    .045       0   194.7      .1       0
Bank Sta=169.5,194.7
XS Rating Curve= 0 ,0
Exp/Cntr(USF)=0,0
Exp/Cntr=0.3,0.1

Type RM Length L Ch R = 1 ,7864    ,337.9,354.9,365.2
XS GIS Cut Line= 3
2189884.00979331658635.1840218692189900.71536475658500.704171781
2189974.21987909658396.294350284
#Sta/Elev= 30
       0 1937.83    10.1 1937.27    22.2  1937.6    30.2 1937.61    34.3 1937.99
    38.3 1937.97    50.4 1937.14    62.5 1935.65    74.6 1933.78    78.6 1932.51
    82.6 1931.45    90.7 1930.89    98.8 1931.34   105.9 1932.21   114.9 1933.42
   122.9    1934     131 1935.12   139.8 1935.33   144.7  1935.9     175 1937.58
   183.2 1938.45   190.2 1939.69   197.1 1941.19   206.6 1942.66   213.2 1943.91
     223 1945.12   242.6  1949.8   252.3 1953.04   258.2 1954.04   263.2 1954.18
#Mann= 3 ,-1,0
       0      .1       0    78.6    .045       0   105.9      .1       0
Bank Sta=78.6,105.9
XS Rating Curve= 0 ,0
Exp/Cntr(USF)=0,0
Exp/Cntr=0.3,0.1

Type RM Length L Ch R = 1 ,7510    ,194,202.6,207.8
XS GIS Cut Line= 4
2189998.25734022658679.6394036452190058.67582359658655.230707597
2190205.25433974658608.2877048442190282.43767215658591.749536127
#Sta/Elev= 30
       0 1935.42    12.6 1935.47      31 1933.93    40.9 1934.11    58.2  1933.6
    70.9 1933.74    87.7 1934.76    96.1 1934.76   112.9  1932.9   125.5 1930.73
   154.9 1931.12   163.7 1930.56   171.7 1929.66   176.8 1931.16   188.9 1936.08
   192.1 1936.67   201.1 1937.34   204.8 1938.49   209.5 1942.14   213.7 1944.96
   230.2 1953.53     241  1957.3   250.7 1961.18   258.9 1963.81   267.1  1967.3
   271.3  1968.3   283.4 1968.78   287.5  1969.5   294.9 1974.21     298 1975.59
#Mann= 3 ,-1,0
       0      .1       0   163.7    .045       0   176.8      .1       0
Bank Sta=163.7,176.8
XS Rating Curve= 0 ,0
Exp/Cntr(USF)=0,0
Exp/Cntr=0.3,0.1

Type RM Length L Ch R = 1 ,7307    ,338.6,319.5,284.7
XS GIS Cut Line= 3
2190023.57091964658780.4673688582190174.16183305 658818.73195842
2190257.34865198658841.375629101
#Sta/Elev= 30
       0 1933.72     4.4  1933.5    17.1 1933.51    41.9 1932.03    50.1 1932.42
      79 1931.48    87.3 1930.86    95.5 1929.44   103.8  1928.6   107.9 1928.93
   112.1 1929.57   124.4 1929.86   128.6 1929.57   132.6 1928.14   136.8 1926.69
   140.9 1926.45   149.2 1928.37   153.3 1929.23   157.5  1929.5   169.9 1929.03
     174 1929.48   178.6 1931.01   182.3 1932.88   186.5 1933.71   191.6 1933.57
   203.1  1935.1   223.8 1937.17   227.9 1937.73     234 1937.86   241.6 1938.36
#Mann= 3 ,-1,0
       0      .1       0   132.6    .045       0   149.2      .1       0
Bank Sta=132.6,149.2
XS Rating Curve= 0 ,0
Exp/Cntr(USF)=0,0
Exp/Cntr=0.3,0.1

Type RM Length L Ch R = 1 ,6988    ,135.5,135.5,135.2
XS GIS Cut Line= 3
2190150.37106027659161.8200180932190164.22693799659012.402264514
2190174.42708314658961.102577246
#Sta/Elev= 30
       0  1931.8     4.7 1931.57     8.7 1931.09    16.7 1930.64    28.8 1929.49
    36.8 1928.93    56.9  1926.8    64.9 1926.83    68.9 1926.63      77 1925.45
      85 1925.16      93 1925.14    97.1 1924.63   101.5 1922.95   103.9 1922.27
   105.1 1921.93   113.1 1921.24   117.1 1921.27   125.2 1922.01   129.2 1922.86
   133.2  1924.3   137.2 1925.38   145.6 1926.54   161.5    1928   165.6 1928.15
   177.8  1927.9     186 1928.25   190.8 1927.99   198.2 1928.01   202.4 1927.82
#Mann= 3 ,-1,0
       0      .1       0   103.9    .045       0   125.2      .1       0
Bank Sta=103.9,125.2
XS Rating Curve= 0 ,0
Exp/Cntr(USF)=0,0
Exp/Cntr=0.3,0.1

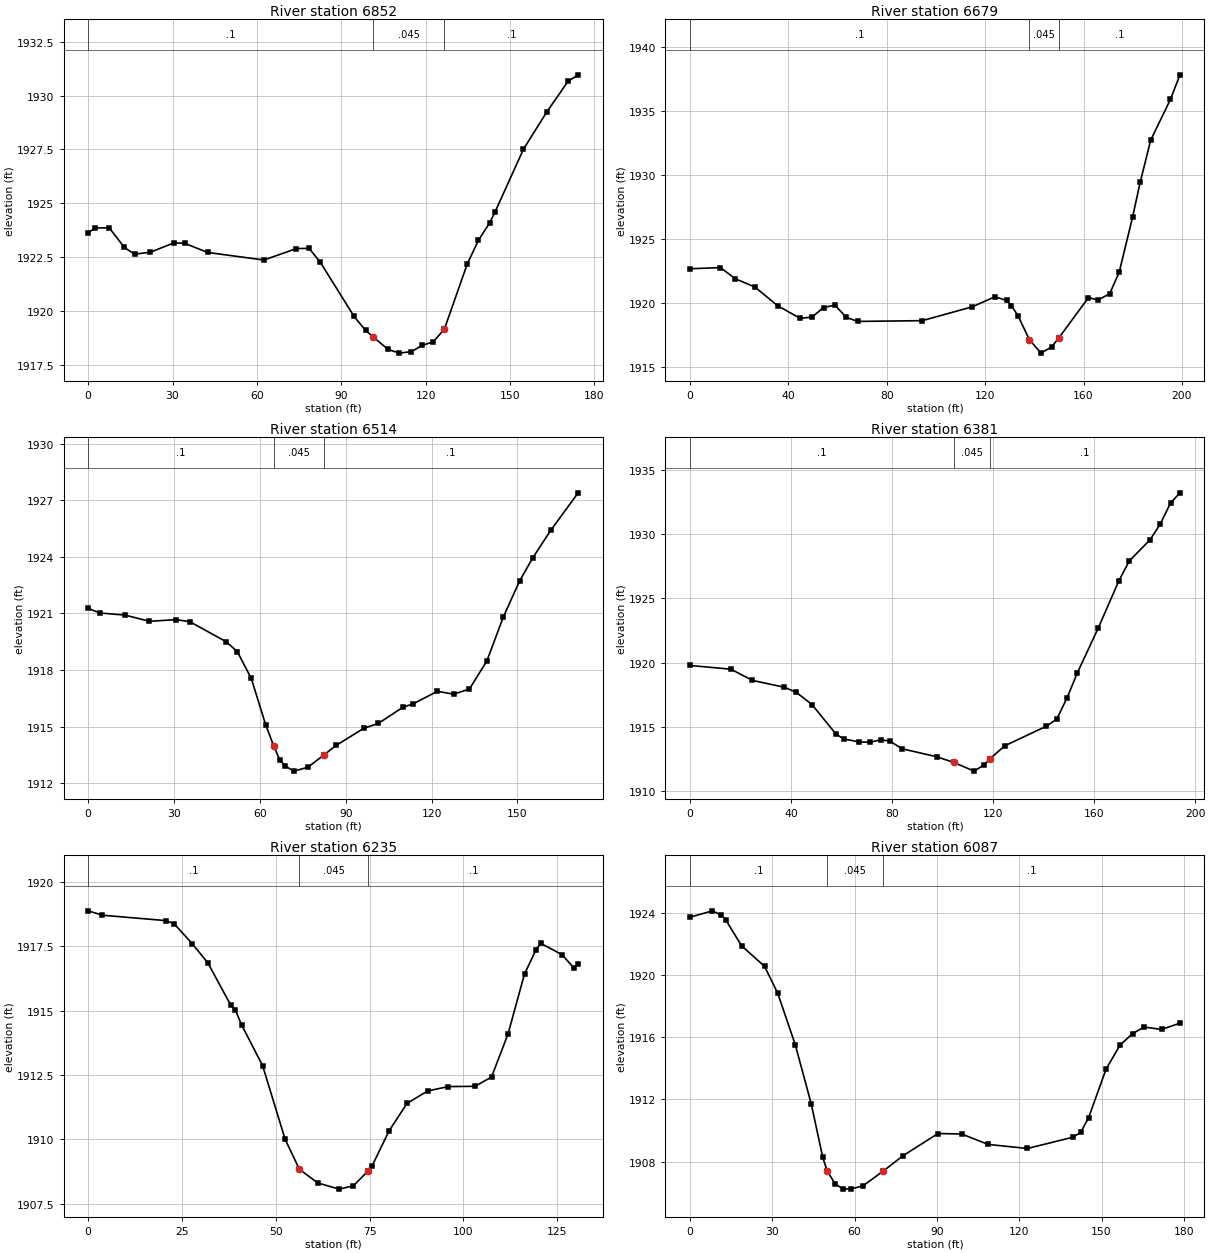
Type RM Length L Ch R = 1 ,6852    ,155.7,172.9,184.8
XS GIS Cut Line= 3
 2190266.4319803659162.7149946992190289.38866179 659137.58342881
2190300.70856495658997.731081541
#Sta/Elev= 30
       0 1923.64     2.6 1923.86     7.5 1923.86    12.9 1922.95    16.5 1922.64
    22.1 1922.73    30.6 1923.17    34.4 1923.14    42.5 1922.72    62.5 1922.37
    74.1  1922.9    78.6 1922.91    82.6 1922.26    94.6 1919.75    98.7  1919.1
   101.3 1918.81   106.7 1918.22   110.7 1918.05     115 1918.12   118.8 1918.41
   122.7 1918.57   126.7 1919.16   134.8 1922.17   138.8 1923.28   142.8 1924.09
   144.7 1924.59   154.8  1927.5   163.2 1929.25   170.7 1930.66   174.3 1930.96
#Mann= 3 ,-1,0
       0      .1       0   101.3    .045       0   126.7      .1       0
Bank Sta=101.3,126.7
XS Rating Curve= 0 ,0
Exp/Cntr(USF)=0,0
Exp/Cntr=0.3,0.1

Type RM Length L Ch R = 1 ,6679    ,171.8,164.8,158.4
XS GIS Cut Line= 3
2190289.50508519659207.8913011142190431.89474556659123.370820866
2190463.26860212659111.196978721
#Sta/Elev= 30
       0 1922.65    12.4 1922.74    18.5 1921.86    26.4 1921.22    35.7 1919.75
    44.8 1918.77    49.6 1918.87    54.3 1919.61    58.9 1919.81    63.6 1918.84
    68.2 1918.53    94.4 1918.59   114.7 1919.67     124 1920.46   128.7 1920.17
   130.7 1919.76   133.3 1918.99     138  1917.1   142.7 1916.05     147 1916.53
   149.9 1917.23     162 1920.39   165.9 1920.21   170.6 1920.69   174.5 1922.39
   179.9 1926.66     183  1929.4   187.3 1932.71   195.3 1935.89   199.2 1937.82
#Mann= 3 ,-1,0
       0      .1       0     138    .045       0   149.9      .1       0
Bank Sta=138,149.9
XS Rating Curve= 0 ,0
Exp/Cntr(USF)=0,0
Exp/Cntr=0.3,0.1

Type RM Length L Ch R = 1 ,6514    ,123.2,133,141.5
XS GIS Cut Line= 4
2190393.92057591659332.6440709272190425.98011277659312.915125169
2190470.37024073659251.2621696722190510.32135589659209.831383579
#Sta/Elev= 30
       0 1921.26     4.2 1921.02    12.9 1920.91    21.4 1920.58    30.8 1920.67
    35.5 1920.56    48.2  1919.5    52.1 1918.98      57 1917.55      62  1915.1
    64.8 1913.99    66.9 1913.24    68.8 1912.92    71.8 1912.64    76.7 1912.84
    82.5 1913.51    86.6    1914    96.3 1914.91   101.4 1915.17   109.9 1916.02
   113.6 1916.21     122 1916.87   127.7 1916.72   133.2 1916.99   139.3 1918.48
     145 1920.79   150.8 1922.74   155.4 1923.96   161.6  1925.4   171.2 1927.39
#Mann= 3 ,-1,0
       0      .1       0    64.8    .045       0    82.5      .1       0
Bank Sta=64.8,82.5
XS Rating Curve= 0 ,0
Exp/Cntr(USF)=0,0
Exp/Cntr=0.3,0.1

Type RM Length L Ch R = 1 ,6381    ,136.7,146.8,155.7
XS GIS Cut Line= 4
2190452.86835646659375.4672496952190531.29091585659347.846725633
2190581.59972753659338.4754763972190639.80011752 659325.15843801
#Sta/Elev= 30
       0 1919.77    16.2 1919.48    24.7 1918.61    37.4 1918.07      42 1917.69
    48.3 1916.73    57.7 1914.45    60.8 1914.05    67.1 1913.81    71.4  1913.8
    75.6 1913.98    79.1 1913.88      84 1913.28    97.7 1912.66   104.4 1912.22
   112.5 1911.54   116.6 1912.05   118.81912.514   124.7 1913.52   141.1 1915.04
   145.2 1915.59   149.3 1917.25   153.4 1919.21   161.6 1922.67   169.8 1926.36
   173.9 1927.91   182.1 1929.55   186.2 1930.79   190.3 1932.44     194 1933.22
#Mann= 3 ,-1,0
       0      .1       0   104.4    .045       0   118.8      .1       0
Bank Sta=104.4,118.8
XS Rating Curve= 0 ,0
Exp/Cntr(USF)=0,0
Exp/Cntr=0.3,0.1

Type RM Length L Ch R = 1 ,6235    ,162.2,147.8,127.8
XS GIS Cut Line= 3
 2190440.9570286659435.786171632 2190517.9747884659485.944796717
2190553.24762798659501.801394325
#Sta/Elev= 30
       0 1918.87     3.8  1918.7    20.7 1918.49    22.9 1918.37    27.7  1917.6
    31.9 1916.85      38 1915.21    39.2 1915.03    40.9 1914.44    46.5 1912.86
    52.5    1910    56.3 1908.84    61.2 1908.31    66.9 1908.07    70.7  1908.2
    74.7 1908.79    75.6 1908.95    80.2 1910.33      85  1911.4    90.5 1911.88
      96 1912.05   103.1 1912.06   107.5 1912.42   111.9 1914.09   116.3 1916.42
   119.3 1917.34   120.6 1917.61   126.3 1917.17   129.4 1916.66   130.6  1916.8
#Mann= 3 ,-1,0
       0      .1       0    56.3    .045       0    74.7      .1       0
Bank Sta=56.3,74.7
XS Rating Curve= 0 ,0
Exp/Cntr(USF)=0,0
Exp/Cntr=0.3,0.1

Type RM Length L Ch R = 1 ,6087    ,150.6,152.3,152
XS GIS Cut Line= 4
2190417.25862168659639.3560882582190478.78333903659599.804484248
2190494.76378509659588.6181720022190566.67579238659541.475856112
#Sta/Elev= 30
       0  1923.7     8.2 1924.11    11.4 1923.83      13 1923.54    18.8 1921.87
    27.2 1920.54      32 1918.81    38.4  1915.5    44.2 1911.71    48.4 1908.28
      50 1907.41    52.9 1906.58    55.8 1906.25    58.7 1906.24    63.2 1906.47
    70.3 1907.38    77.7 1908.39    90.4 1909.81      99 1909.78   108.7 1909.11
     123 1908.85   139.5 1909.57   142.4 1909.88   145.3 1910.83   151.7 1913.96
   156.8  1915.5   161.3 1916.22   165.5 1916.65   171.9 1916.49   178.6  1916.9
#Mann= 3 ,-1,0
       0      .1       0      50    .045       0    70.3      .1       0
Bank Sta=50,70.3
XS Rating Curve= 0 ,0
Exp/Cntr(USF)=0,0
Exp/Cntr=0.3,0.1

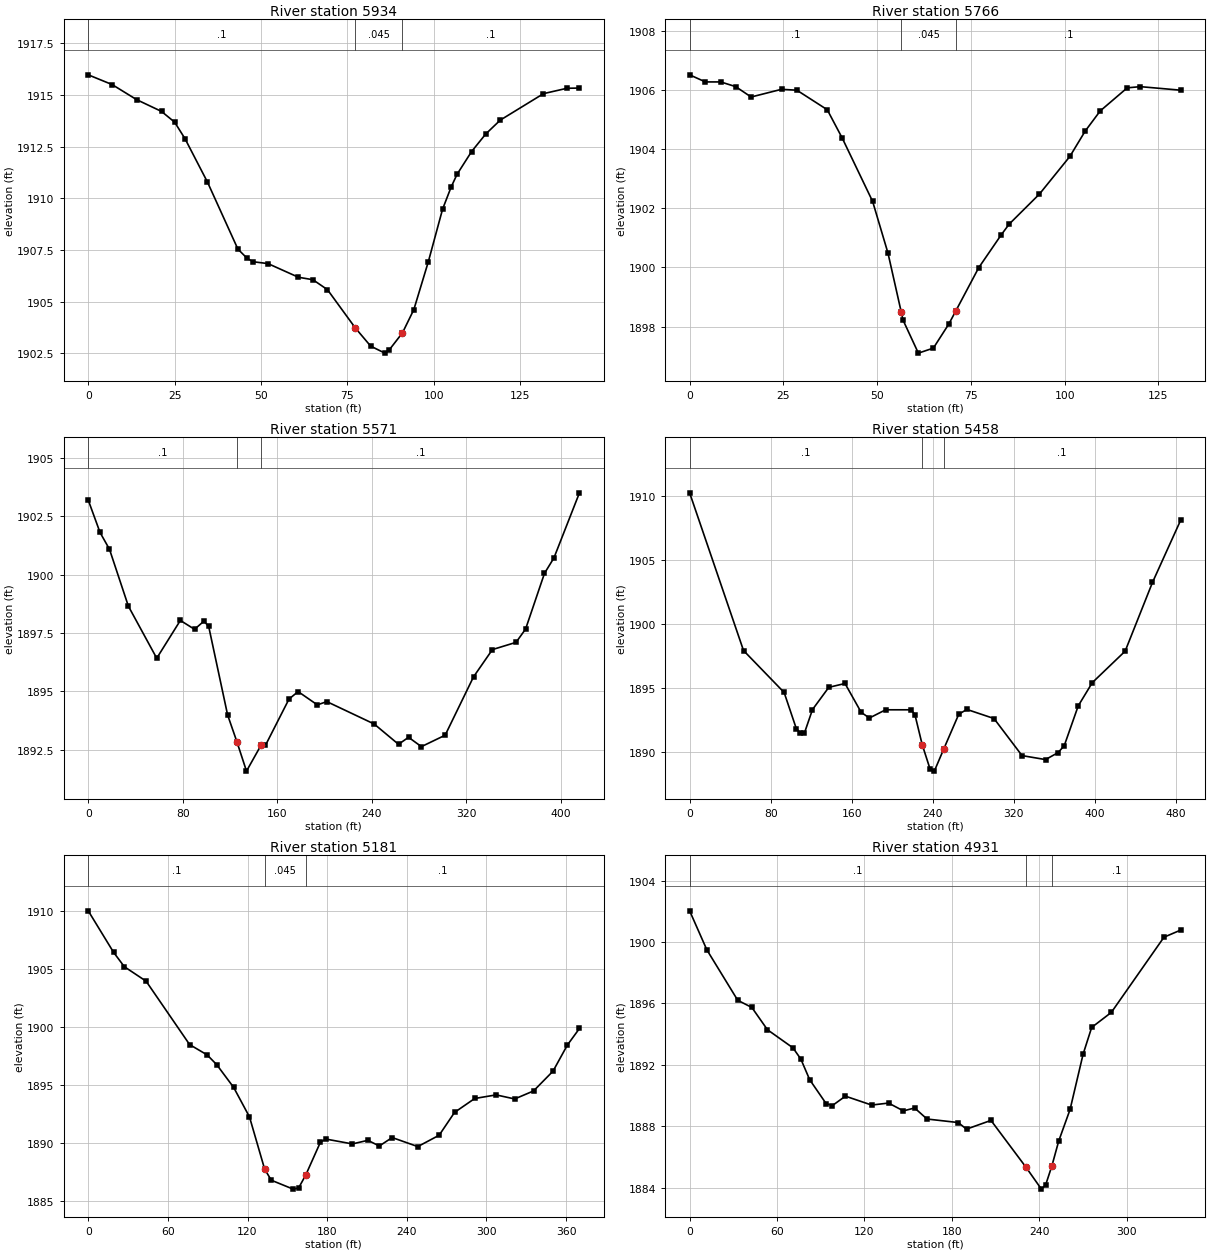
Type RM Length L Ch R = 1 ,5934    ,165.9,168.8,168.9
XS GIS Cut Line= 3
 2190516.9056364659695.0384869722190570.61769122659670.180015316
2190650.07602027659646.653247498
#Sta/Elev= 30
       0 1915.97     6.9  1915.5      14 1914.77    21.2  1914.2      25 1913.68
      28 1912.88    34.5 1910.78    43.3 1907.54      46 1907.09    47.7 1906.93
      52 1906.84    60.8 1906.18      65 1906.06    69.2 1905.58    77.3 1903.72
    81.7 1902.85    85.8 1902.51      87 1902.65    90.9 1903.49    94.2 1904.62
    98.4 1906.94   102.5 1909.47     105 1910.55   106.7 1911.16   110.9 1912.26
     115 1913.11   119.2 1913.78   131.7 1915.06   138.5 1915.32   142.1 1915.33
#Mann= 3 ,-1,0
       0      .1       0    77.3    .045       0    90.9      .1       0
Bank Sta=77.3,90.9
XS Rating Curve= 0 ,0
Exp/Cntr(USF)=0,0
Exp/Cntr=0.3,0.1

Type RM Length L Ch R = 1 ,5766    ,191.5,194.7,195.8
XS GIS Cut Line= 4
2190575.99681264659826.2427352582190624.73717314659818.252512226
2190666.68584406  659811.86033382190705.43842577659806.267177677
#Sta/Elev= 27
       0 1906.51     4.2 1906.27     8.3 1906.27    12.3 1906.11    16.4 1905.76
    24.5 1906.02    28.6 1905.99    36.7 1905.33    40.7 1904.37    48.8 1902.23
    52.9 1900.48    56.41898.507    56.9 1898.22      61  1897.1      65 1897.27
    69.1 1898.08      711898.531    77.1 1899.99    83.1  1901.1    85.2 1901.46
    93.3 1902.48   101.4 1903.75   105.5 1904.61   109.5 1905.29   116.7 1906.07
   120.2 1906.11     131 1905.99
#Mann= 3 ,-1,0
       0      .1       0    56.4    .045       0      71      .1       0
Bank Sta=56.4,71
XS Rating Curve= 0 ,0
Exp/Cntr(USF)=0,0
Exp/Cntr=0.3,0.1

Type RM Length L Ch R = 1 ,5571    ,111.3,112.8,113.4
XS GIS Cut Line= 3
2190526.20583166660005.9216392552190710.86876396660005.477737976
2190941.69742934660018.350875083
#Sta/Elev= 30
       0  1903.2      10 1901.81      18 1901.09      34 1898.65      58 1896.42
      78 1898.04      90 1897.66      98 1898.01     102 1897.78     118 1893.99
     126 1892.82     134 1891.58   146.4  1892.7     150 1892.68     170 1894.67
   177.7 1894.99     194 1894.42     202 1894.56   242.1  1893.6   262.7 1892.73
   271.2 1893.03   282.1 1892.63   302.2 1893.12   326.2 1895.62   342.2 1896.79
   362.2  1897.1   370.3 1897.67   386.3 1900.06   394.3 1900.72   415.9 1903.51
#Mann= 3 ,-1,0
       0      .1       0     126    .045       0   146.4      .1       0
Bank Sta=126,146.4
XS Rating Curve= 0 ,0
Exp/Cntr(USF)=0,0
Exp/Cntr=0.3,0.1

Type RM Length L Ch R = 1 ,5458    ,278.5,277.1,276.6
XS GIS Cut Line= 3
2190419.10176192660101.6417620432190698.45603988660120.203508086
 2190875.7207146660223.221198629
#Sta/Elev= 30
       0 1910.23    53.2 1897.94    93.3 1894.67   105.3 1891.86   109.3 1891.51
   113.3  1891.5   121.3 1893.34   137.4 1895.07   153.4 1895.37   169.4 1893.12
   177.5 1892.68   193.5 1893.32   218.6 1893.32   222.4 1892.95   229.6 1890.61
   237.4  1888.7   241.6 1888.54   250.7 1890.23   265.7 1892.97   273.7 1893.35
   300.5 1892.64   328.2 1889.75   351.4 1889.44   363.9 1889.99   369.9 1890.53
   383.7 1893.63   397.6 1895.44     430 1897.89     457 1903.25     485 1908.13
#Mann= 3 ,-1,0
       0      .1       0   229.6    .045       0   250.7      .1       0
Bank Sta=229.6,250.7
XS Rating Curve= 0 ,0
Exp/Cntr=0.3,0.1

Type RM Length L Ch R = 1 ,5181    ,236.3,249.6,252.6
XS GIS Cut Line= 4
2190361.56034919660237.1425081622190455.29716671 660257.56042881
 2190537.8969366660277.0502621562190678.96620654660403.270135254
#Sta/Elev= 30
       0 1910.05    19.1 1906.47    27.2 1905.23    43.6 1903.98    76.4 1898.51
    89.6 1897.62    96.8 1896.78   109.6 1894.81   121.5 1892.27   132.9 1887.77
   137.9 1886.81   154.4 1886.04   158.5 1886.14   163.9 1887.26   174.9 1890.08
     179 1890.36     199 1889.94   210.7 1890.25   219.3 1889.76     229 1890.49
   248.3 1889.71   264.4 1890.69     276 1892.66   291.2 1893.86   307.3 1894.17
   321.3 1893.82   335.5 1894.51   350.2 1896.22     361 1898.47   370.1  1899.9
#Mann= 3 ,-1,0
       0      .1       0   132.9    .045       0   163.9      .1       0
Bank Sta=132.9,163.9
XS Rating Curve= 0 ,0
Exp/Cntr=0.3,0.1

Type RM Length L Ch R = 1 ,4931    ,208.3,183,157.6
XS GIS Cut Line= 3
2190408.20418374660276.7589776922190536.83708382660417.921056354
2190604.49464815 660547.38923501
#Sta/Elev= 30
       0 1902.04    11.8  1899.5      33 1896.21    42.7 1895.74    53.4 1894.29
    70.9 1893.11    76.3 1892.38    82.4 1891.03    93.7 1889.47      98 1889.35
   106.9 1889.96   124.9 1889.38   136.5 1889.51   146.7    1889   154.4 1889.19
   162.9 1888.47   184.3 1888.24     190 1887.81   206.8 1888.38   230.8 1885.33
   241.4  1883.9   244.3 1884.17   248.61885.417   253.3 1887.04   261.1  1889.1
     270 1892.69   275.9 1894.44   289.4 1895.42   325.5 1900.32   337.1 1900.79
#Mann= 3 ,-1,0
       0      .1       0   230.8    .045       0   248.6      .1       0
Bank Sta=230.8,248.6
XS Rating Curve= 0 ,0
Exp/Cntr(USF)=0,0
Exp/Cntr=0.3,0.1

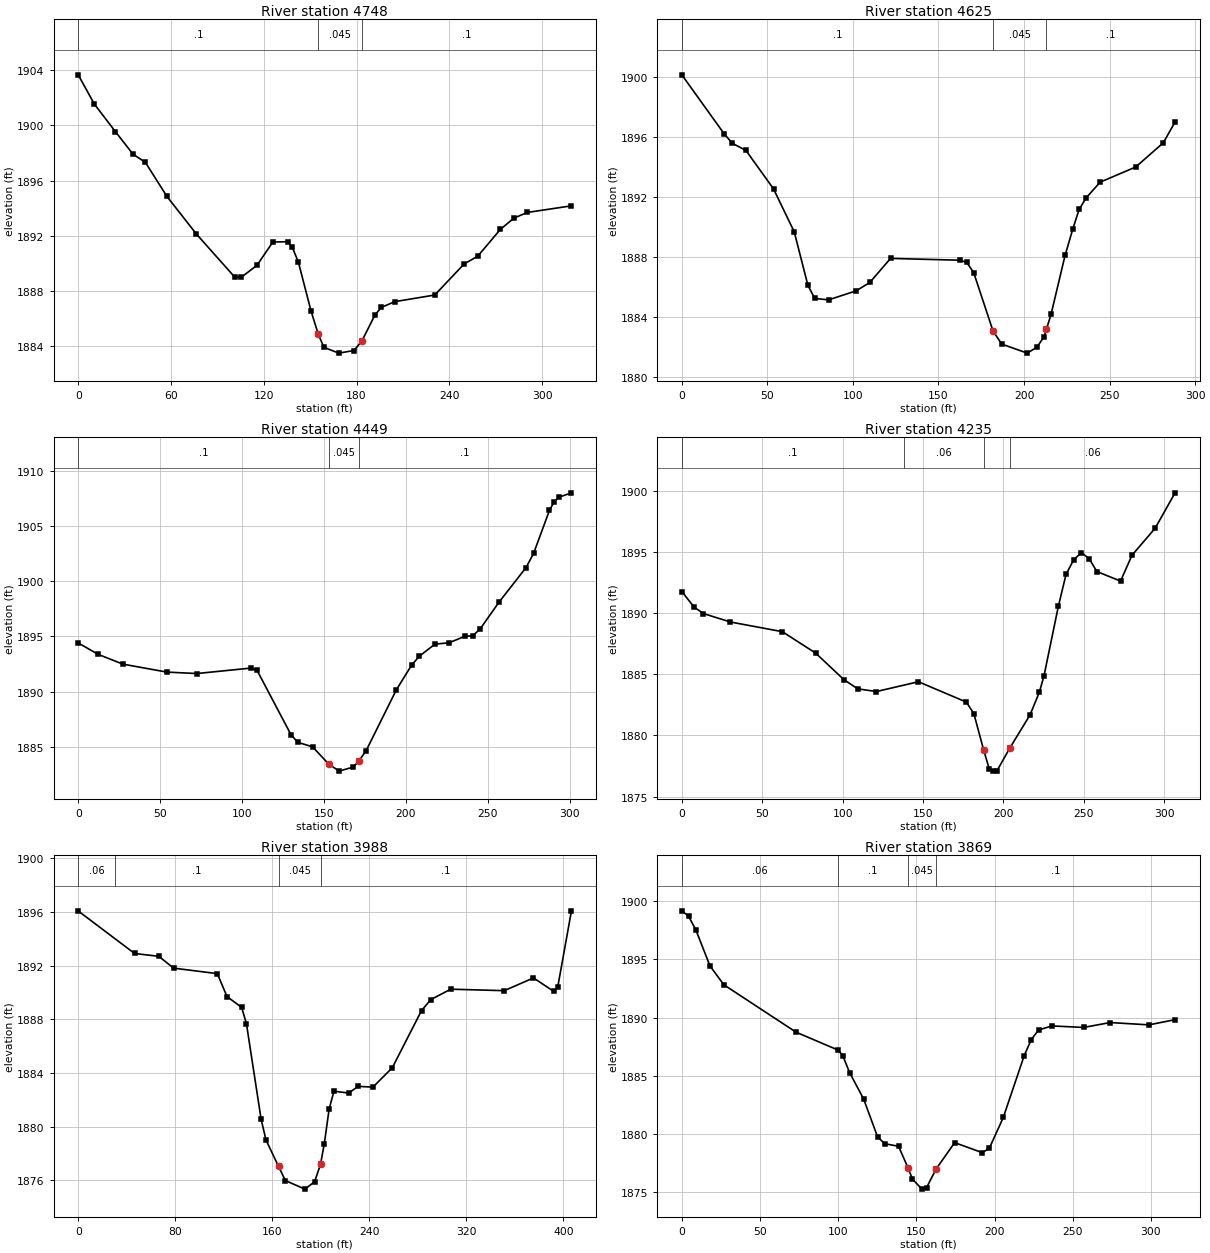
Type RM Length L Ch R = 1 ,4748    ,122.3,123.1,124
XS GIS Cut Line= 3
2190253.95360179660546.9758464512190462.25764073660495.415440774
2190553.00395472660546.975846451
#Sta/Elev= 30
       0 1903.66    10.5 1901.53    24.1 1899.54    35.3 1897.93    43.5 1897.31
    57.4 1894.85    76.5 1892.12   101.2 1889.01   105.3 1888.98   115.6 1889.86
   125.9 1891.55   135.4 1891.57   138.3 1891.21   142.4 1890.09   150.6 1886.54
   155.3 1884.86   158.9 1883.92   168.5  1883.5   178.4 1883.69   183.6 1884.41
   191.8 1886.24     196 1886.81   204.8 1887.23   230.6 1887.71   249.6 1889.96
   258.4 1890.52     273 1892.46   281.8 1893.28   290.4 1893.69     319 1894.17
#Mann= 3 ,-1,0
       0      .1       0   155.3    .045       0   183.6      .1       0
Bank Sta=155.3,183.6
XS Rating Curve= 0 ,0
Exp/Cntr(USF)=0,0
Exp/Cntr=0.3,0.1

Type RM Length L Ch R = 1 ,4625    ,159.3,176.3,188.2
XS GIS Cut Line= 3
2190282.87344119660607.2394081332190433.22358415 660623.01689227
2190566.86815566660592.390011298
#Sta/Elev= 30
       0 1900.16    24.8 1896.22    29.5  1895.6    37.5 1895.12    53.6 1892.56
    65.7  1889.7    73.7 1886.13    77.7 1885.26    85.8 1885.17   101.9 1885.77
   109.9 1886.33     122 1887.93   162.4 1887.81   166.5 1887.67   170.6 1886.98
   181.9 1883.09     187 1882.22   201.9 1881.62   207.6 1882.02   211.7 1882.71
   213.1 1883.21   215.8  1884.2     224 1888.13   228.6 1889.92   232.2 1891.19
   236.3 1891.96   244.5 1893.01   265.3 1894.02   281.4 1895.63   288.3 1897.02
#Mann= 3 ,-1,0
       0      .1       0   181.9    .045       0   213.1      .1       0
Bank Sta=181.9,213.1
XS Rating Curve= 0 ,0
Exp/Cntr(USF)=0,0
Exp/Cntr=0.3,0.1

Type RM Length L Ch R = 1 ,4449    ,209.7,214.4,220.7
XS GIS Cut Line= 3
2190273.56790556660705.215176658 2190405.6461836 660735.15062521
2190548.03209152660819.706810518
#Sta/Elev= 30
       0  1894.4    12.2 1893.36    27.3 1892.48    54.1 1891.76    72.4 1891.63
   105.2 1892.12   109.1 1891.93   129.8 1886.11   133.9 1885.41     143    1885
   152.8 1883.45   159.2  1882.8   167.9 1883.17   171.2 1883.71   175.6 1884.62
   194.2 1890.17   203.5  1892.4   208.2  1893.2   217.7 1894.29   226.3 1894.41
   236.1 1895.01   240.7 1895.03   245.4 1895.69   256.9 1898.11   273.3 1901.22
   277.9  1902.5   287.6  1906.4   290.5 1907.19   293.5 1907.59     301 1907.98
#Mann= 3 ,-1,0
       0      .1       0   152.8    .045       0   171.2      .1       0
Bank Sta=152.8,171.2
XS Rating Curve= 0 ,0
Exp/Cntr=0.3,0.1

Type RM Length L Ch R = 1 ,4235    ,273,246.8,228.7
XS GIS Cut Line= 4
2190214.41983621660816.4841820422190332.28692358660888.874991613
2190396.32494743660987.2522456442190425.82895735661028.844306224
#Sta/Elev= 30
       0 1891.75     7.6 1890.48    13.4 1889.95    30.2 1889.26    62.5 1888.47
    83.2 1886.72   100.7 1884.56   109.4  1883.8     121 1883.58   147.1 1884.38
   176.9 1882.72   181.6 1881.77   187.6 1878.84   191.2 1877.23   193.4 1877.08
     196 1877.12   204.1    1879   216.5 1881.67   222.3 1883.52   225.2 1884.87
   234.1 1890.53   238.9 1893.15   243.7 1894.35   248.5 1894.93   253.2 1894.44
   258.1 1893.38   272.8  1892.6   279.9 1894.71   294.3 1896.92   306.7 1899.81
#Mann= 4 ,-1,0
       0      .1       0  138.32     .06       0   187.6    .045       0
   204.1     .06       0
Bank Sta=187.6,204.1
XS Rating Curve= 0 ,0
Exp/Cntr=0.3,0.1

Type RM Length L Ch R = 1 ,3988    ,129.8,118.8,109.7
XS GIS Cut Line= 3
 2189969.8058138661027.6985194312190196.46754339661044.077354741
2190375.41433846661057.488976045
#Sta/Elev= 30
       0 1896.07    46.5  1892.9    66.5 1892.69    78.6 1891.81   114.7  1891.4
   122.7 1889.69   134.7 1888.89   138.7 1887.68   150.8 1880.56   154.8 1879.01
   165.2 1877.03   170.8 1875.98   186.9 1875.34   194.9 1875.89   199.8 1877.19
   202.9 1878.71   206.9 1881.31   210.9 1882.64   222.9  1882.5     231    1883
     243 1882.94     259 1884.39   283.1 1888.65   290.8 1889.47   307.2 1890.24
   351.3 1890.13   375.4 1891.08   392.2 1890.07   395.4  1890.4   406.7 1896.08
#Mann= 4 ,-1,0
       0     .06       0      30      .1       0   165.2    .045       0
   199.8      .1       0
Bank Sta=165.2,199.8
XS Rating Curve= 0 ,0
Exp/Cntr=0.3,0.1

Type RM Length L Ch R = 1 ,3869    ,150.7,143.8,134.1
XS GIS Cut Line= 3
2190040.10563949661223.0790813892190249.76056106661118.669259892
2190328.27674682661097.787295593
#Sta/Elev= 30
       0 1899.17     4.3 1898.71       9 1897.52      18 1894.44    26.9 1892.82
    73.1 1888.75    99.9 1887.22   102.9 1886.75   107.3 1885.29   116.3 1883.01
   125.2 1879.77   129.7 1879.18   138.6 1878.96   144.7  1877.1   147.5 1876.14
   153.6 1875.28   156.5  1875.4   162.6    1877   174.5 1879.27   192.2 1878.41
   196.7 1878.79   205.6 1881.43     219 1886.74   223.5 1888.12   228.2 1888.94
   236.7 1889.29     257 1889.16     274 1889.58   298.8 1889.38   315.5 1889.83
#Mann= 4 ,-1,0
       0     .06       0     100      .1       0   144.7    .045       0
   162.6      .1       0
Bank Sta=144.7,162.6
XS Rating Curve= 0 ,0
Exp/Cntr=0.3,0.1