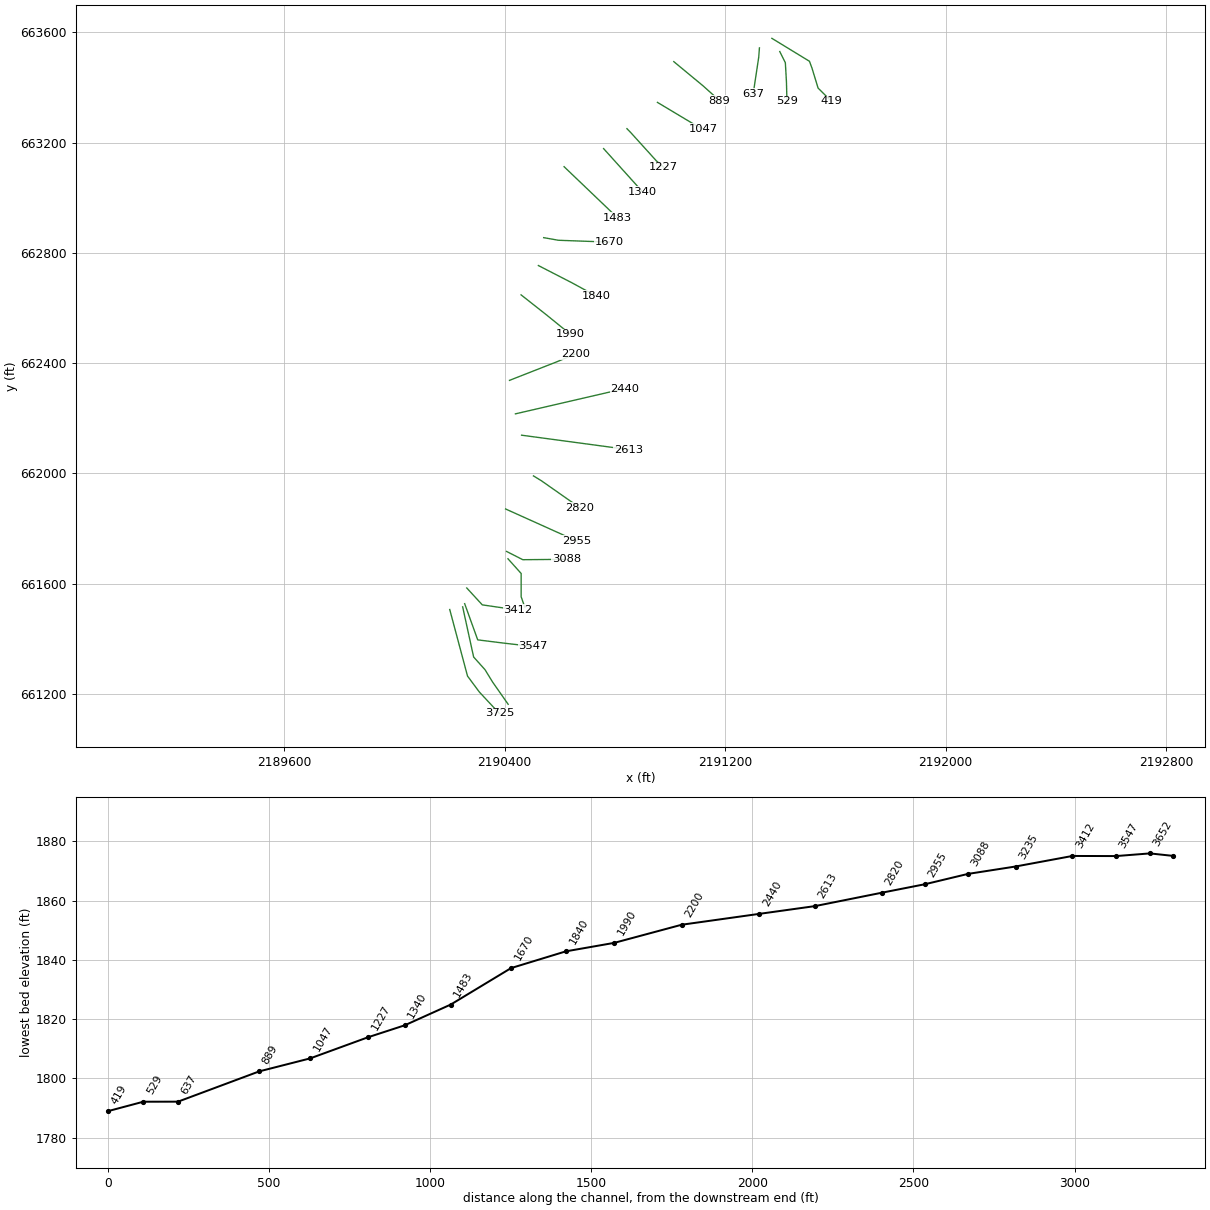
HEC-RAS study BIGRN.prj: BIGRN

--- BIGRN.g01 (geometry) --- (continued)

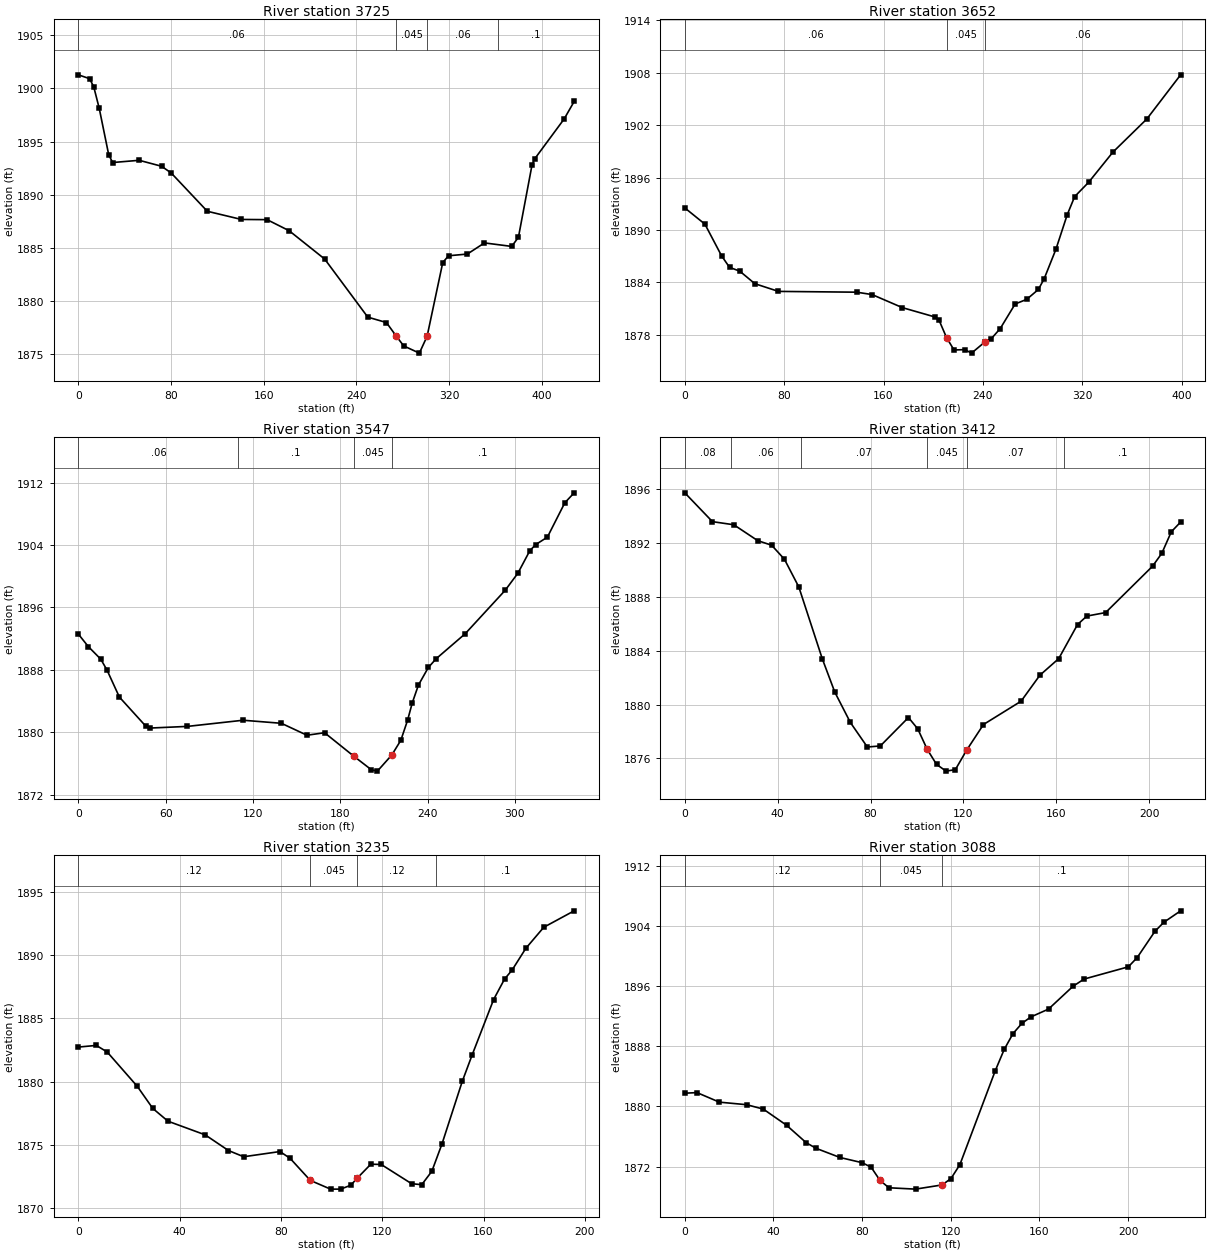
Type RM Length L Ch R = 1 ,3725    ,73.9,73.1,77.4
XS GIS Cut Line= 4
2190201.22459841661506.5224330692190265.68118714661265.209939815
2190308.80875357661207.0378734752190381.02235316661129.809440574
#Sta/Elev= 30
       0 1901.28     9.7 1900.92    13.3 1900.15      18 1898.14    26.2 1893.76
    29.6 1893.02    52.5 1893.23    71.8 1892.67    80.1 1892.04   111.3 1888.43
   140.7 1887.66   162.9 1887.64   181.9  1886.6   212.6 1883.93   249.8 1878.46
   265.9 1877.95   274.1 1876.71   280.8 1875.75   294.3 1875.07     301 1876.66
   314.5  1883.6   319.5 1884.24   335.7  1884.4   350.5 1885.45     374 1885.12
   379.8 1885.98   391.5 1892.77   393.8 1893.36   419.3 1897.13   427.9 1898.77
#Mann= 4 ,-1,0
       0     .06       0   274.1    .045       0     301     .06       0
  362.19      .1       0
Bank Sta=274.1,301
XS Rating Curve= 0 ,0
Exp/Cntr=0.3,0.1

Type RM Length L Ch R = 1 ,3652    ,87.9,105.2,115.2
XS GIS Cut Line= 5
2190248.06625418 661516.316093192190287.88027953661334.325596047
2190329.18920892 661288.240746492190356.72339963661243.340321979
2190413.11728632661162.907340389
#Sta/Elev= 30
       0 1892.53    16.2 1890.67    29.6 1887.05      36 1885.73    44.2  1885.3
    56.4 1883.86    75.4 1882.98   138.3 1882.89   150.7 1882.62   175.2 1881.12
   201.5 1880.05   204.7 1879.67   210.7 1877.69   216.7 1876.28   225.4 1876.32
   230.8 1875.92   241.6  1877.2   246.7 1877.57   253.9 1878.73   265.9 1881.54
   275.2 1882.07   284.6  1883.2   289.3 1884.44   298.7 1887.79   307.8 1891.74
   313.8 1893.82     325 1895.45   344.6 1898.91   371.9  1902.7   399.1 1907.75
#Mann= 3 ,-1,0
       0     .06       0   210.7    .045       0   241.6     .06       0
Bank Sta=210.7,241.6
XS Rating Curve= 0 ,0
Exp/Cntr=0.3,0.1

Type RM Length L Ch R = 1 ,3547    ,133.1,135,135.9
XS GIS Cut Line= 4
2190255.37458637 661527.677908622190302.70481137661396.458317856
2190401.83817813661384.080742337 2190502.4570043661372.606771177
#Sta/Elev= 30
       0 1892.58     6.9 1890.97    15.4 1889.37    19.7 1887.97    28.2 1884.51
    46.3 1880.79    49.4 1880.54    74.9 1880.75   113.2 1881.54   139.5 1881.15
   157.1 1879.62   169.2 1879.94   189.3 1876.93   201.4 1875.19   205.5 1875.02
   215.4 1877.09   221.6 1878.97   226.2 1881.52   229.5 1883.79   233.7 1886.05
   240.5  1888.3   245.8 1889.41   265.8 1892.62   293.3 1898.19     302 1900.37
   310.2 1903.25   314.2 1904.04   322.3    1905   334.3 1909.41   340.7 1910.68
#Mann= 4 ,-1,0
       0     .06       0     110      .1       0   189.3    .045       0
   215.4      .1       0
Bank Sta=189.3,215.4
XS Rating Curve= 0 ,0
Exp/Cntr=0.3,0.1

Type RM Length L Ch R = 1 ,3412    ,197.4,176.6,158.3
XS GIS Cut Line= 3
2190262.94396432661584.7245116112190319.39067024661523.345569251
2190448.17684394661504.712676035
#Sta/Elev= 30
       0 1895.72    11.9 1893.58    21.1 1893.35    31.4 1892.17    37.4 1891.83
    42.9 1890.79    49.1 1888.73    59.2  1883.4    64.6 1880.92    71.3 1878.67
    78.6 1876.85    84.2 1876.93    96.3 1879.04   100.3  1878.2   104.4 1876.67
   108.4 1875.56   112.5 1875.06   116.5 1875.17   121.3  1876.6   128.6 1878.52
   144.8 1880.25   152.9 1882.18     161 1883.41   169.1 1885.94   173.1 1886.57
   181.2 1886.83   201.4 1890.27   205.4 1891.23   209.5 1892.83   213.5 1893.55
#Mann= 6 ,-1,0
       0     .08       0      20     .06       0      50     .07       0
   104.4    .045       0   121.3     .07       0  163.39      .1       0
Bank Sta=104.4,121.3
XS Rating Curve= 0 ,0
Exp/Cntr(USF)=0,0
Exp/Cntr=0.3,0.1

Type RM Length L Ch R = 1 ,3235    ,107.1,147.7,168.3
XS GIS Cut Line= 4
2190412.55513632661690.493581927 2190460.2334219661637.335033633
 2190460.2334219661552.9389878892190473.38605241661515.125175185
#Sta/Elev= 30
       0 1882.73     7.1 1882.86    11.4 1882.34    23.3 1879.62    29.4 1877.88
    35.4 1876.87    50.1 1875.79    59.3 1874.55    65.3 1874.06    79.6 1874.47
    83.6 1873.94    91.6 1872.19    99.6  1871.5   103.6  1871.5   107.6 1871.81
   110.11872.361   115.5 1873.47   119.6 1873.45   131.6 1871.93   135.6 1871.85
   139.6 1872.91   143.6 1875.07   151.6 1880.01   155.5  1882.1     164 1886.49
   168.3  1888.1   171.3 1888.82   176.7 1890.53   183.8  1892.2   195.8  1893.5
#Mann= 4 ,-1,0
       0     .12       0    91.6    .045       0   110.1     .12       0
  141.41      .1       0
Bank Sta=91.6,110.1
XS Rating Curve= 0 ,0
Exp/Cntr=0.3,0.1

Type RM Length L Ch R = 1 ,3088    ,138.4,132.6,123.8
XS GIS Cut Line= 3
2190407.28511322661717.2401206082190466.22410238 661687.26702283
2190623.81765736661688.594393914
#Sta/Elev= 30
       0 1881.76     5.5 1881.84    15.6 1880.57    27.9 1880.23    35.4 1879.65
    45.9  1877.5    54.8 1875.17    59.3 1874.42      70 1873.21    80.1 1872.51
    84.1  1871.9    88.1 1870.15    92.1 1869.18   104.1    1869   116.1 1869.56
   120.1 1870.41   124.1 1872.25   140.1 1884.77   144.1 1887.58   148.1  1889.7
   152.1 1891.05   156.1  1891.9   164.1 1892.95   175.1 1895.97   180.1 1896.94
   200.1 1898.57   204.1  1899.8   212.1 1903.29   216.1 1904.49   223.7 1906.02
#Mann= 3 ,-1,0
       0     .12       0    88.1    .045       0   116.1      .1       0
Bank Sta=88.1,116.1
XS Rating Curve= 0 ,0
Exp/Cntr=0.3,0.1

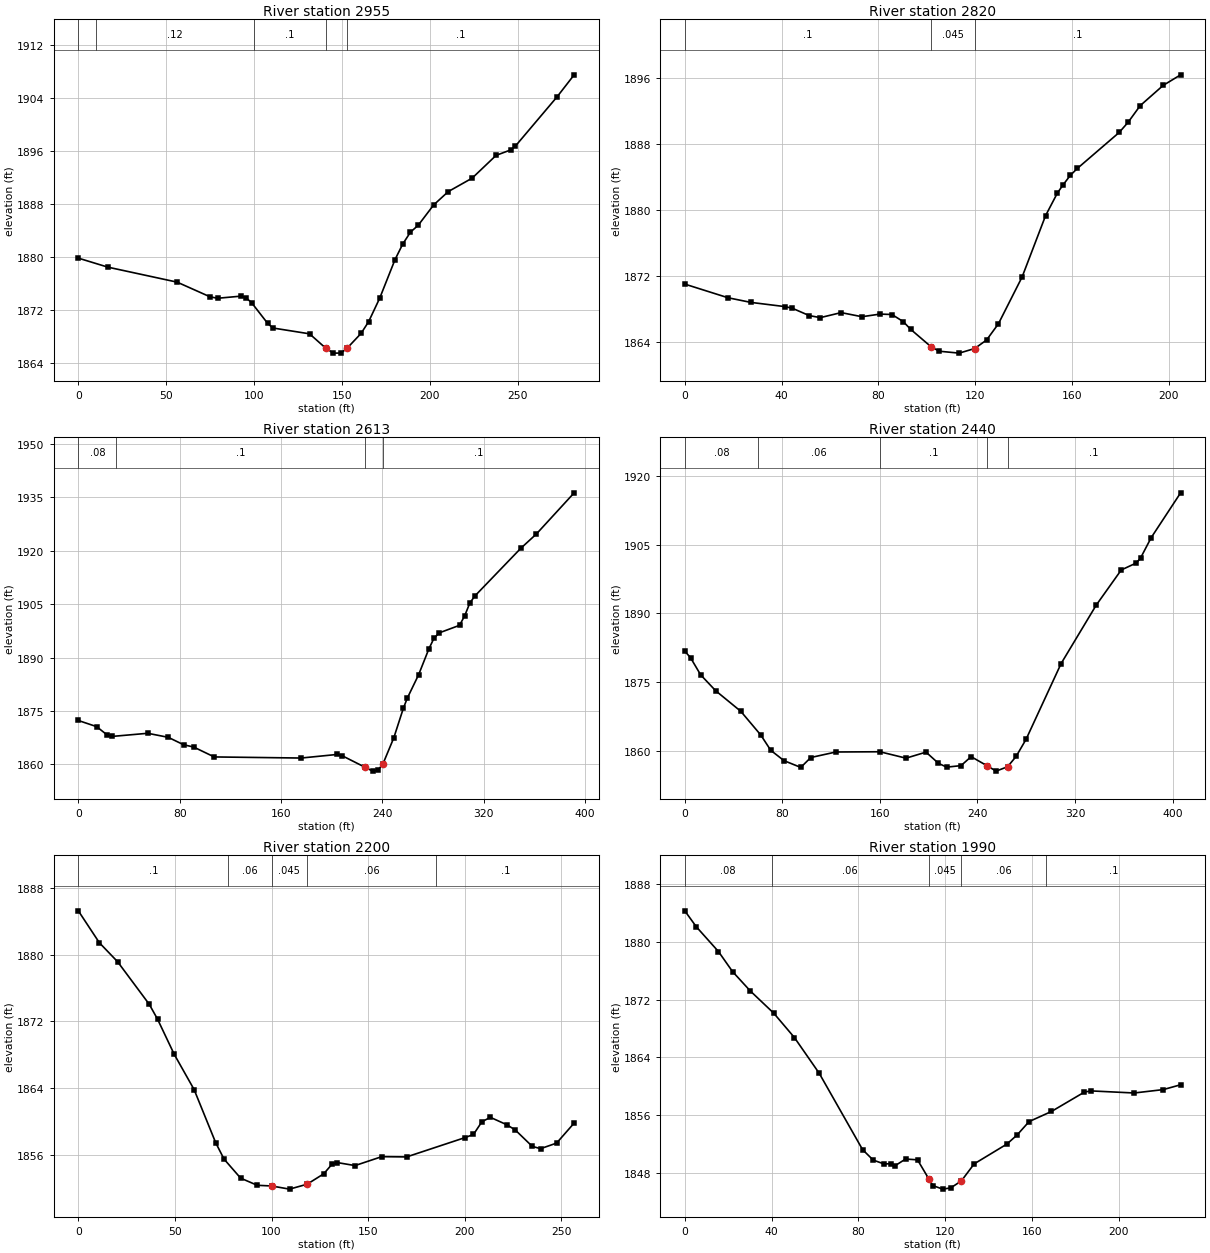
Type RM Length L Ch R = 1 ,2955    ,137.2,134.9,131.9
XS GIS Cut Line= 2
 2190403.9158464661871.1890356732190661.01459085661755.419425599
#Sta/Elev= 30
       0 1879.86    16.8  1878.5    56.2 1876.24    74.9 1874.03    79.2 1873.81
    92.5 1874.13    95.5 1873.85    98.5 1873.16   107.6 1870.05   110.6 1869.33
   131.5 1868.45   140.7 1866.29     145 1865.54   149.4 1865.55     153 1866.32
   160.8 1868.51   165.1 1870.28   171.4 1873.82   180.1 1879.63   184.5 1881.98
   188.9 1883.78   193.3 1884.81   202.1 1887.88   210.4 1889.89     224 1891.92
   237.6 1895.35   245.9 1896.17   248.4 1896.69   272.3 1904.18     282 1907.49
#Mann= 5 ,-1,0
       0      .1       0      10     .12       0     100      .1       0
   140.7    .045       0     153      .1       0
Bank Sta=140.7,153
XS Rating Curve= 0 ,0
Exp/Cntr=0.3,0.1

Type RM Length L Ch R = 1 ,2820    ,200.3,206.9,212.3
XS GIS Cut Line= 4
2190504.90986104661991.2467910132190533.96872005661973.427132882
2190636.95856798661901.2590642642190674.12110134661875.704846229
#Sta/Elev= 30
       0 1871.03    17.9 1869.37    27.3 1868.81    41.6 1868.29    44.5 1868.09
    51.4 1867.21      56 1866.96    64.6 1867.57    73.2 1867.07    80.7 1867.39
    85.6 1867.34    90.3 1866.47    93.3 1865.55   101.9 1863.39   105.2 1862.88
   113.4 1862.65   119.8 1863.21   124.7 1864.24   129.6 1866.21   139.4  1871.9
   149.1 1879.35     154  1882.1   156.3 1883.07   159.3 1884.23   162.2 1885.07
   179.5 1889.44   183.2 1890.68   188.2  1892.7   197.7 1895.16   204.9 1896.44
#Mann= 3 ,-1,0
       0      .1       0   101.9    .045       0   119.8      .1       0
Bank Sta=101.9,119.8
XS Rating Curve= 0 ,0
Exp/Cntr=0.3,0.1

Type RM Length L Ch R = 1 ,2613    ,165.6,172.9,175.2
XS GIS Cut Line= 2
2190461.84576997662138.8684082232190849.80917802662086.700735545
#Sta/Elev= 30
       0 1872.34    14.5 1870.61    22.5 1868.35    26.6 1867.87    54.8 1868.75
      71 1867.62    83.1 1865.54    91.1 1864.89   107.3 1862.12   175.9 1861.81
   204.2 1862.81   208.2 1862.48   226.21859.259   232.4 1858.14   236.4 1858.34
   240.5 1860.15   249.1 1867.49   256.6 1875.73   259.7 1878.57   268.7 1885.18
   276.8 1892.44   280.8 1895.39   284.9  1896.9     301 1899.03   305.1 1901.72
   309.1 1905.27   313.1 1907.25   349.4 1920.64   361.6 1924.61   391.5 1936.18
#Mann= 4 ,-1,0
       0     .08       0      30      .1       0   226.2    .045       0
   240.5      .1       0
Bank Sta=226.2,240.5
XS Rating Curve= 0 ,0
Exp/Cntr=0.3,0.1

Type RM Length L Ch R = 1 ,2440    ,240.7,240.9,244.8
XS GIS Cut Line= 3
2190439.49478097662216.249921327     2190688.246      662273.851
2190835.66740765662307.963508529
#Sta/Elev= 30
       0 1881.72     4.7 1880.29      13 1876.55    25.3 1873.08    45.9 1868.59
    62.3 1863.41    70.5 1860.06    81.4  1857.8    95.1 1856.33   103.3 1858.49
   123.9  1859.7     160 1859.75   181.4 1858.35   197.8 1859.67     208 1857.23
   214.7 1856.39   226.5 1856.72   234.8 1858.68   247.81856.704   255.3 1855.52
   264.7 1856.48   271.7 1858.73   279.9 1862.49   308.6 1879.02   337.4 1891.78
   357.9 1899.45   370.2 1900.97   373.7 1902.04   382.5 1906.53   406.6  1916.3
#Mann= 5 ,-1,0
       0     .08       0      60     .06       0     160      .1       0
   247.8    .045       0   264.7      .1       0
Bank Sta=247.8,264.7
XS Rating Curve= 0 ,0
Exp/Cntr=0.3,0.1

Type RM Length L Ch R = 1 ,2200    ,224.7,209.4,197
XS GIS Cut Line= 4
2190417.99471053662337.7328368342190443.70458497662347.881471483
2190590.52149956662405.3904011632190656.14933696662433.130002538
#Sta/Elev= 30
       0 1885.29    10.9 1881.45    20.3 1879.18    36.7 1874.06      41 1872.27
    49.6 1868.06    59.9 1863.82    71.1 1857.42    75.4 1855.46      84 1853.17
    92.6 1852.31     100 1852.23   109.3 1851.85   118.4 1852.44     127 1853.69
   131.2 1854.82     134 1855.04   143.2 1854.68     157 1855.75   169.9 1855.72
   200.1 1858.04   204.5 1858.42   208.8 1859.93   213.2 1860.48   221.9 1859.57
   226.2 1858.94   234.9 1856.99   239.2 1856.71   247.5 1857.38   256.6 1859.79
#Mann= 5 ,-1,0
       0      .1       0   77.64     .06       0     100    .045       0
   118.4     .06       0  185.32      .1       0
Bank Sta=100,118.4
XS Rating Curve= 0 ,0
Exp/Cntr(USF)=0,0
Exp/Cntr=0.3,0.1

Type RM Length L Ch R = 1 ,1990    ,146.7,149.9,153.3
XS GIS Cut Line= 3
2190460.00208444 662647.893941582190551.57885324662575.732163331
 2190638.3845773 662505.24876795
#Sta/Elev= 30
       0 1884.29     5.3 1882.08    15.5 1878.65      22 1875.87    30.2 1873.18
      41  1870.1    50.5 1866.73    61.9 1861.79    81.9  1851.2    86.8 1849.75
    91.9 1849.21    94.9 1849.26      97    1849   101.7  1849.9   107.2 1849.79
   112.3  1847.2   114.3 1846.22   118.8 1845.73   122.5  1845.9   127.4 1846.87
   133.3 1849.23   148.3 1851.96     153 1853.21   158.6 1855.09   168.9 1856.49
   184.1 1859.18   187.1 1859.34     207 1859.05   220.4 1859.52   228.4 1860.19
#Mann= 5 ,-1,0
       0     .08       0      40     .06       0   112.3    .045       0
   127.4     .06       0  166.59      .1       0
Bank Sta=112.3,127.4
XS Rating Curve= 0 ,0
Exp/Cntr=0.3,0.1

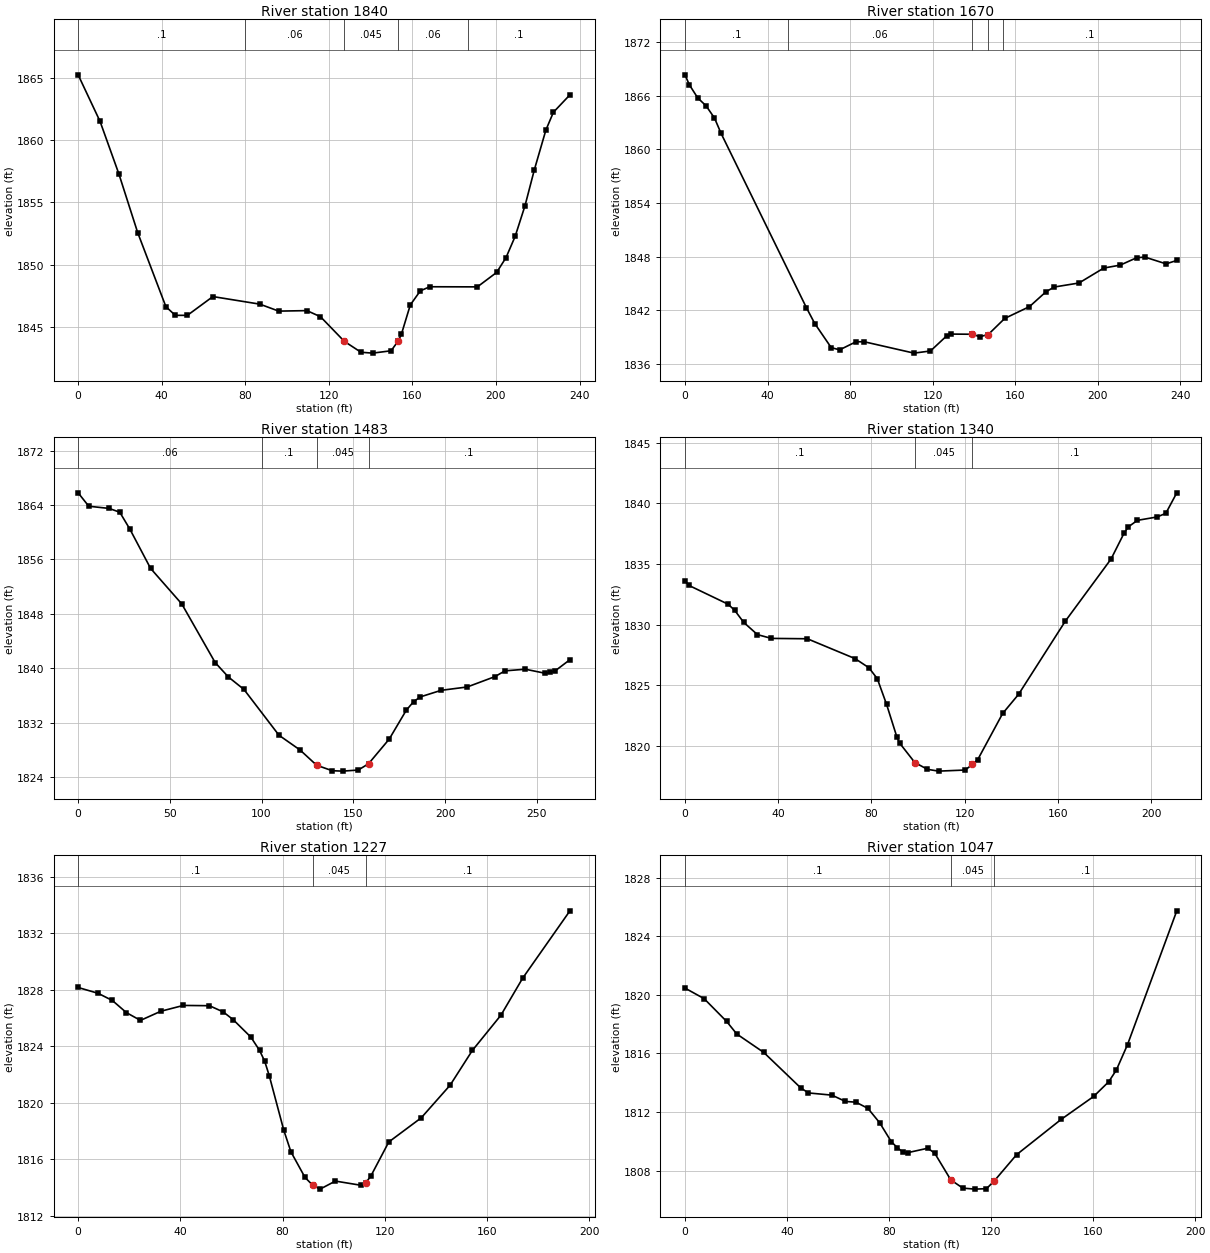
Type RM Length L Ch R = 1 ,1840    ,164.5,170.1,175.9
XS GIS Cut Line= 3
2190522.84310483662754.249538207     2190644.508      662691.669
2190731.07805282662644.493933851
#Sta/Elev= 30
       0 1865.26    10.5 1861.51    19.5 1857.29    28.5 1852.57      42 1846.61
    46.5 1845.91    52.3 1845.91    64.5 1847.42      87 1846.81      96 1846.25
   109.5 1846.29     116  1845.8   127.4 1843.82   135.4 1842.94     141 1842.87
   149.8 1843.06   153.1 1843.82   154.7 1844.37     159 1846.75   163.8 1847.88
   168.3 1848.21   191.1  1848.2   200.3 1849.36   204.8 1850.55   209.2 1852.27
   213.9 1854.73   218.4 1857.64   223.9 1860.82   227.5 1862.25   235.4 1863.65
#Mann= 5 ,-1,0
       0      .1       0      80     .06       0   127.4    .045       0
   153.1     .06       0  186.82      .1       0
Bank Sta=127.4,153.1
XS Rating Curve= 0 ,0
Exp/Cntr=0.3,0.1

Type RM Length L Ch R = 1 ,1670    ,199.1,187.3,173.8
XS GIS Cut Line= 3
2190542.08792313662855.4351844152190595.53739895662845.963125409
2190779.56597393662839.197368976
#Sta/Elev= 30
       0 1868.33     2.1 1867.22     6.2 1865.74    10.2 1864.87    14.3  1863.5
    17.5 1861.78    58.9 1842.28    62.9 1840.53    70.9 1837.83      75 1837.59
    82.9 1838.49    86.9 1838.49     111 1837.22     119 1837.46     127 1839.18
     129 1839.35     139 1839.33     143 1839.06     147  1839.3     155  1841.1
     167 1842.42     175 1844.08     179 1844.61     191 1845.06     203 1846.73
     211 1847.06     219 1847.89     223 1847.95   233.2  1847.2   238.4 1847.58
#Mann= 5 ,-1,0
       0      .1       0      50     .06       0     139    .045       0
     147     .06       0  154.28      .1       0
Bank Sta=139,147
XS Rating Curve= 0 ,0
Exp/Cntr=0.3,0.1

Type RM Length L Ch R = 1 ,1483    ,143.4,142.7,140.2
XS GIS Cut Line= 2
2190615.98225055663112.8362023132190809.77581922662927.529943227
#Sta/Elev= 30
       0 1865.79     5.8 1863.82    16.9  1863.5    22.7 1862.94    28.2 1860.46
    39.5 1854.69    56.5 1849.47    74.7 1840.86    81.9 1838.74    90.4 1836.91
   109.5 1830.18     121 1828.01     130 1825.78   138.5 1824.97   144.2 1824.91
   152.7 1825.07   158.3 1825.99   169.6 1829.62   178.9 1833.86   182.9 1835.12
   186.6 1835.82   197.9 1836.78   212.1 1837.27   227.2 1838.79   232.7 1839.64
   243.8 1839.88   254.5 1839.29   257.3  1839.4   260.2 1839.67   268.1 1841.28
#Mann= 4 ,-1,0
       0     .06       0     100      .1       0     130    .045       0
   158.3      .1       0
Bank Sta=130,158.3
XS Rating Curve= 0 ,0
Exp/Cntr=0.3,0.1

Type RM Length L Ch R = 1 ,1340    ,112.8,113.5,113.1
XS GIS Cut Line= 2
2190759.32759058663178.4398660152190900.60310214663021.696232757
#Sta/Elev= 30
       0  1833.6     1.7 1833.23    18.5 1831.68    21.3 1831.18    25.2 1830.18
    31.1 1829.17    37.1 1828.86    52.5 1828.83      73 1827.19    78.9 1826.44
    82.5 1825.54    86.5 1823.41    90.9 1820.73    92.1 1820.22    98.6 1818.62
     104 1818.06   108.8 1817.91   120.2    1818   123.3 1818.46   125.6 1818.86
   136.3 1822.67   143.1 1824.24   163.2 1830.29   182.8 1835.41   188.4 1837.55
   190.2 1838.06   194.1  1838.6   202.6 1838.88   206.3 1839.18     211 1840.87
#Mann= 3 ,-1,0
       0      .1       0    98.6    .045       0   123.3      .1       0
Bank Sta=98.6,123.3
XS Rating Curve= 0 ,0
Exp/Cntr=0.3,0.1

Type RM Length L Ch R = 1 ,1227    ,176.1,179.8,183.4
XS GIS Cut Line= 4
2190843.99584057663250.7443320192190857.69621475663236.697008643
2190950.82977553663133.9577442892190976.50001929663111.370090311
#Sta/Elev= 30
       0 1828.17     7.8 1827.76    13.4 1827.25    18.9 1826.39    24.4 1825.84
    32.4 1826.49    41.2  1826.9    51.4 1826.88    56.8 1826.44    60.7 1825.89
    67.6 1824.66      71 1823.72      73 1822.96    74.8 1821.93    80.5 1818.06
    83.3 1816.53    88.8 1814.72    91.8 1814.17    94.7 1813.89   100.7 1814.46
   110.8 1814.16   112.6 1814.35   114.5 1814.79   121.6 1817.23   134.3 1818.94
   145.6 1821.25   154.3 1823.71   165.5 1826.21     174 1828.83   192.5  1833.6
#Mann= 3 ,-1,0
       0      .1       0    91.8    .045       0   112.6      .1       0
Bank Sta=91.8,112.6
XS Rating Curve= 0 ,0
Exp/Cntr=0.3,0.1

Type RM Length L Ch R = 1 ,1047    ,161.6,158.2,157.8
XS GIS Cut Line= 3
2190954.72692964663346.0492978972191093.42442092663263.037044755
2191121.78264404663250.146943336
#Sta/Elev= 30
       0 1820.46     7.5 1819.74    16.3 1818.19    20.3 1817.33    30.9 1816.07
    45.4 1813.65    48.4 1813.31    57.6 1813.16    62.9 1812.73      67 1812.68
    71.7 1812.26    76.3 1811.28    80.9 1809.98    83.3 1809.57    85.6 1809.25
    87.4 1809.24    95.2 1809.54    97.9  1809.2   104.2 1807.38   108.9 1806.82
   113.6 1806.75   118.2 1806.78   121.3 1807.32     130  1809.1   147.5 1811.51
   160.2 1813.07   166.1 1814.07   169.1 1814.87   173.5 1816.61   192.8 1825.73
#Mann= 3 ,-1,0
       0      .1       0   104.2    .045       0   121.3      .1       0
Bank Sta=104.2,121.3
XS Rating Curve= 0 ,0
Exp/Cntr=0.3,0.1

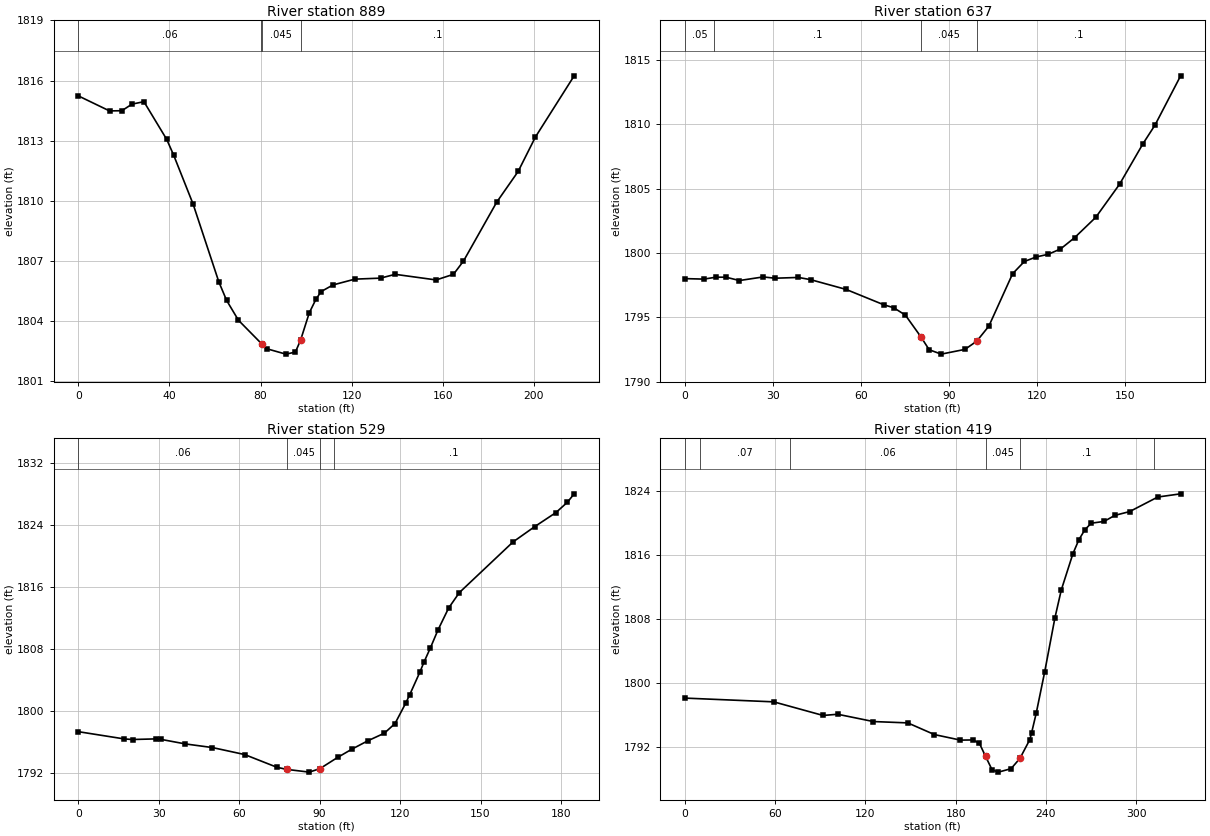
Type RM Length L Ch R = 1 ,889     ,267,252,239
XS GIS Cut Line= 3
2191013.98047776663493.8778550022191119.63525747663406.559855242
2191179.66078634663352.720681929
#Sta/Elev= 30
       0 1815.24    13.7 1814.49    19.1  1814.5    23.6 1814.83    28.8 1814.95
    38.8 1813.07    41.8  1812.3    50.4 1809.84    61.7 1805.96    65.1 1805.04
    70.3 1804.05    80.7 1802.85    82.7 1802.63    91.1 1802.36    95.3 1802.46
    97.61803.064   101.4 1804.42   104.3 1805.09   106.6 1805.48   111.8 1805.81
   121.4  1806.1   132.7 1806.15   139.1 1806.34   157.1 1806.06   164.7 1806.34
   169.1    1807   183.7 1809.94   193.1 1811.47   200.7 1813.19   217.7 1816.24
#Mann= 4 ,-1,0
       0     .06       0      80      .1       0    80.7    .045       0
    97.6      .1       0
Bank Sta=80.7,97.6
XS Rating Curve= 0 ,0
Exp/Cntr=0.3,0.1

Type RM Length L Ch R = 1 ,637     ,105.3,107.6,110.8
XS GIS Cut Line= 3
2191324.58397989663543.7618403212191322.11786167663510.715856176
2191301.89569227663376.559025018
#Sta/Elev= 30
       0 1798.01     6.5 1797.97    10.6 1798.12      14 1798.12    18.6 1797.86
    26.7 1798.14    30.7 1798.04    38.7  1798.1    42.8 1797.93    54.9 1797.17
    67.8 1795.97    71.1 1795.75    75.1 1795.17    80.3 1793.51    83.2 1792.48
    87.3 1792.14    95.4 1792.51    99.4 1793.15   103.5 1794.31   111.6 1798.39
   115.6 1799.34   119.6 1799.69   123.7  1799.9   127.9 1800.31   132.7 1801.19
   139.9 1802.77     148 1805.34     156  1808.5   160.1 1809.95   168.8 1813.77
#Mann= 4 ,-1,0
       0     .05       0      10      .1       0    80.3    .045       0
    99.4      .1       0
Bank Sta=80.3,99.4
XS Rating Curve= 0 ,0
Exp/Cntr=0.3,0.1

Type RM Length L Ch R = 1 ,529     ,105.5,110.7,114.5
XS GIS Cut Line= 4
2191398.35169886663530.4096200012191418.57386826663489.965281196
2191422.51965741663422.3936419732191424.49255199663350.382989955
#Sta/Elev= 30
       0 1797.34    17.2  1796.4    20.2 1796.33    29.1 1796.41    30.9 1796.34
    39.9 1795.76      50 1795.29      62 1794.39    74.1 1792.74    77.8 1792.47
    86.1 1792.12    90.1 1792.57    96.7 1794.02   102.1  1795.1     108 1796.17
   114.1 1797.14   118.1 1798.39   122.1 1801.03   123.5 1802.05   127.4 1805.05
   128.9 1806.32   131.3 1808.16   134.1 1810.45   138.1  1813.3   142.1 1815.29
   162.1 1821.82   170.2  1823.8   178.1 1825.61   182.4 1826.95   184.9 1828.03
#Mann= 4 ,-1,0
       0     .06       0    77.8    .045       0    90.1     .06       0
   95.22      .1       0
Bank Sta=77.8,90.1
XS Rating Curve= 0 ,0
Exp/Cntr(USF)=0,0
Exp/Cntr=0.3,0.1

Type RM Length L Ch R = 1 ,419     ,103.8,118.7,136.1
XS GIS Cut Line= 5
2191369.71251916663578.4308459072191506.01803763663495.250464596
2191515.42661546 663469.79986062 2191537.3476663663397.947527302
2191585.45219454663350.451917143
#Sta/Elev= 30
       0 1798.16    59.1 1797.69    91.9 1795.99   101.6 1796.14   125.3 1795.23
   148.2 1795.06   165.9  1793.6   183.2 1792.91   191.6 1792.93   195.8  1792.5
   199.91790.865   204.2  1789.2   208.4 1788.91   216.8 1789.34   222.7 1790.62
   229.3 1792.98   230.5 1793.85   233.5 1796.24   239.2 1801.47     246 1808.22
   250.2 1811.67   257.9 1816.19   261.9 1817.95   265.9  1819.2   270.1 1820.01
   278.6 1820.23   285.8 1820.99   295.6 1821.46   314.3 1823.28   329.5 1823.68
#Mann= 6 ,-1,0
       0     .05       0      10     .07       0      70     .06       0
   199.9    .045       0   222.7      .1       0  311.94     .03       0
Bank Sta=199.9,222.7
XS Rating Curve= 0 ,0
Exp/Cntr(USF)=0,0
Exp/Cntr=0.3,0.1