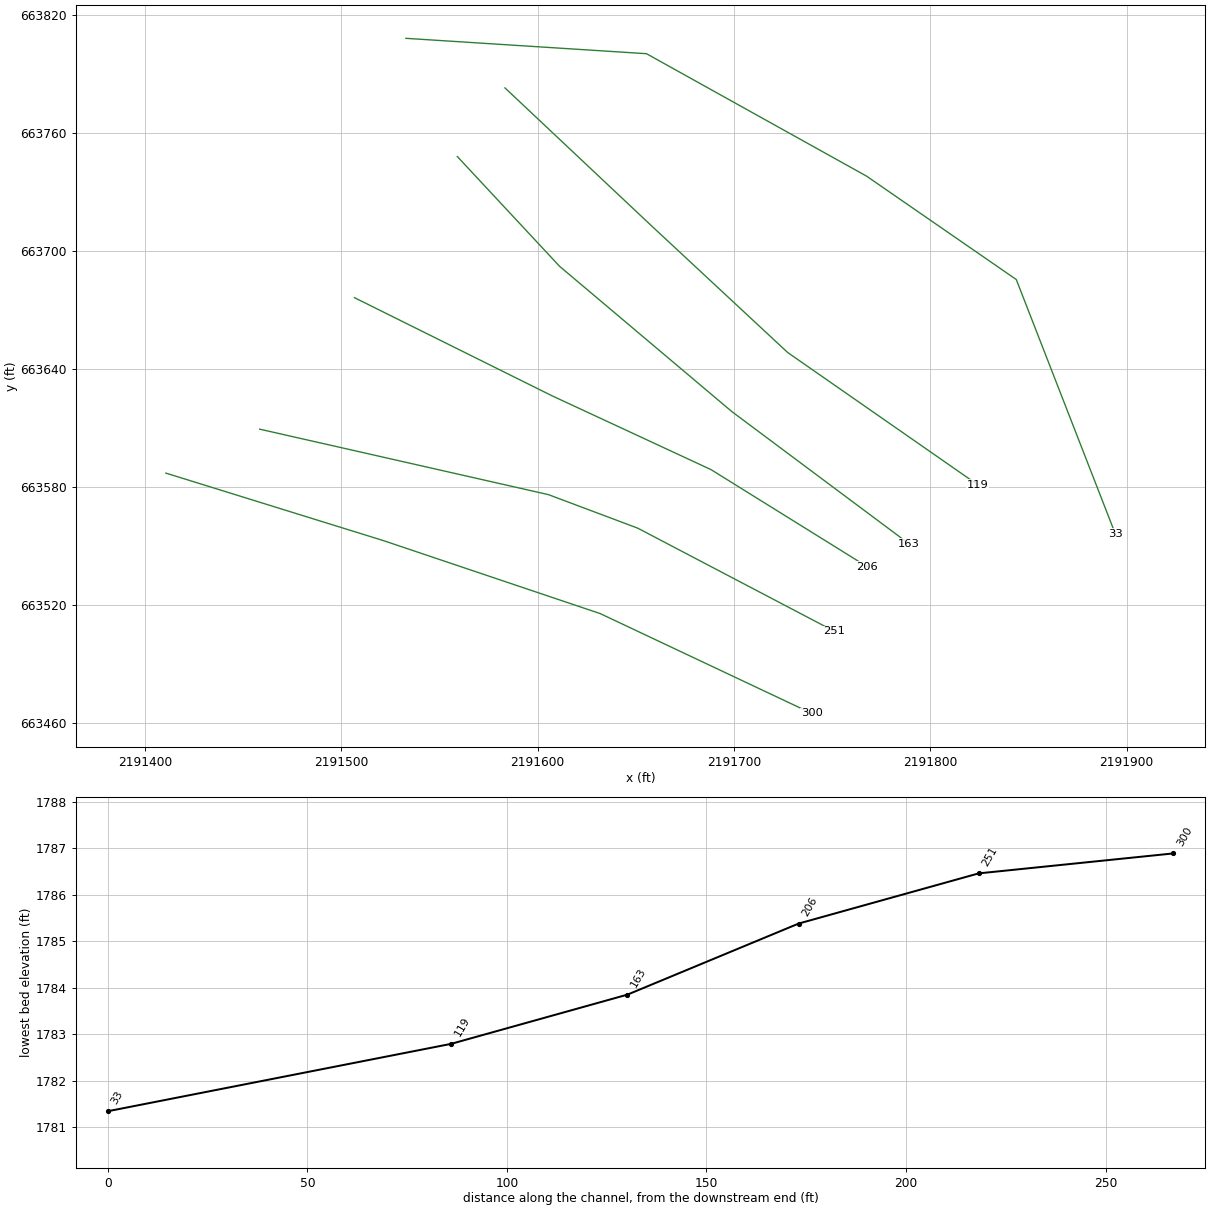
HEC-RAS study BIGRN.prj: BIGRN

--- BIGRN.g01 (geometry) --- (continued)

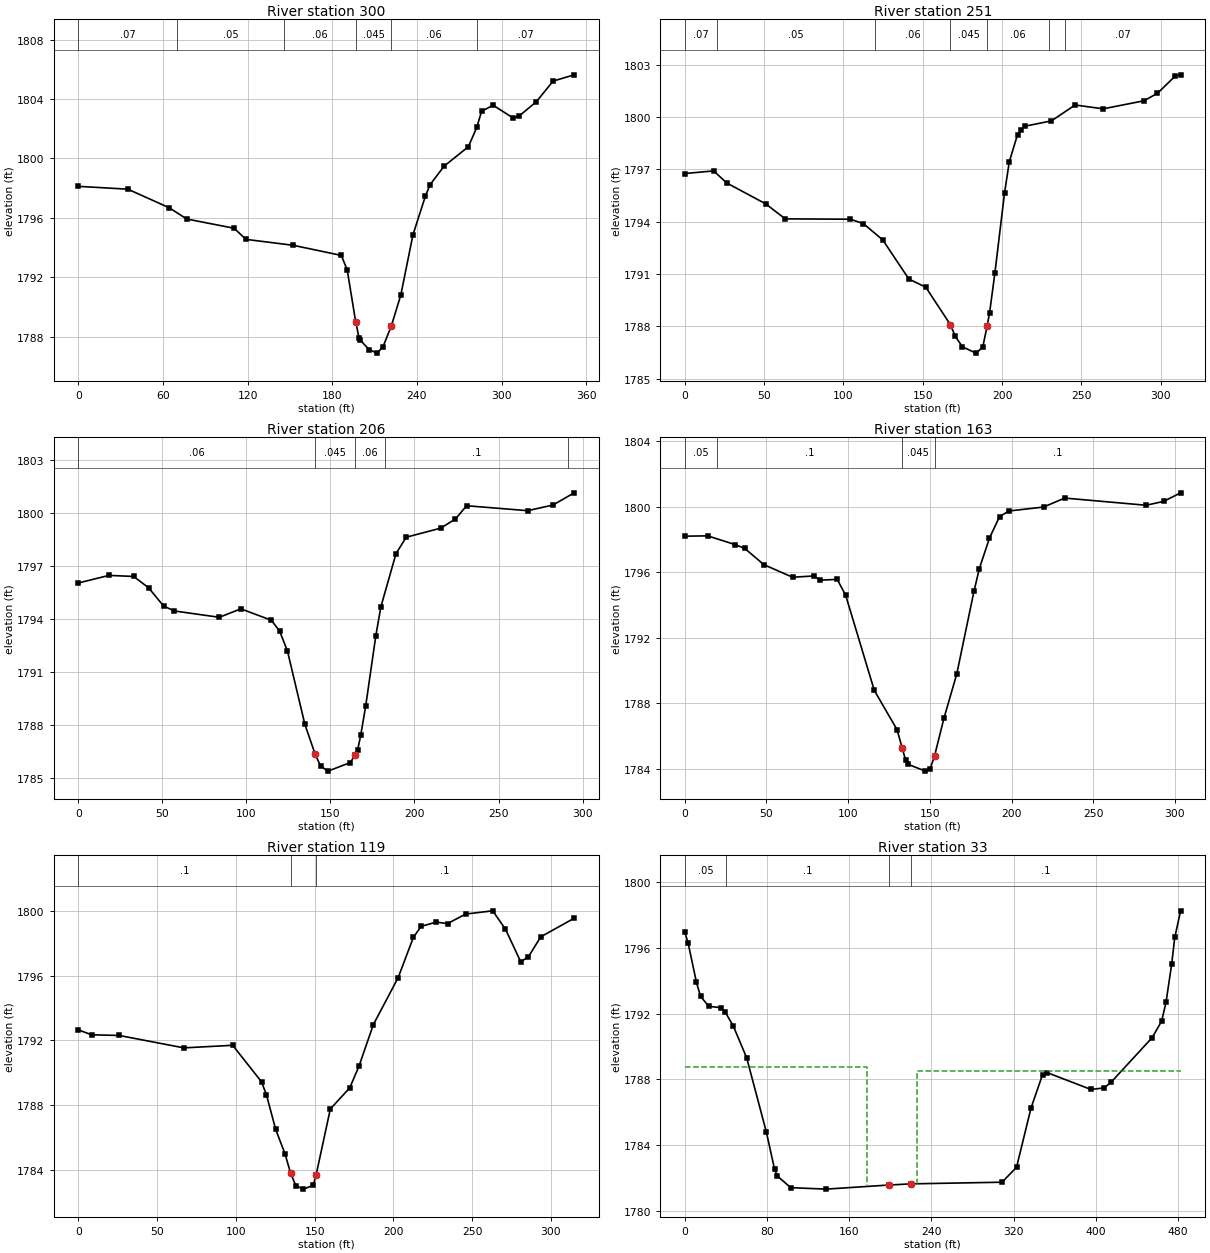
Type RM Length L Ch R = 1 ,300     ,49.2,48.8,47.8
XS GIS Cut Line= 4
2191410.69525667663586.9200347462191521.55950417663552.553312496
2191631.88583689663515.4435460382191739.59305577663464.674835082
#Sta/Elev= 30
       0 1798.12    35.1 1797.93    64.4 1796.68    76.9 1795.92   110.4  1795.3
   118.8 1794.55   152.4 1794.15   186.4 1793.47   190.6  1792.5   196.6 1789.01
     199 1787.91   199.7 1787.78   206.1 1787.13   211.7 1786.89   215.9  1787.3
   221.9 1788.72   228.6  1790.8   237.2 1794.85   246.1 1797.48   249.4 1798.24
   259.3 1799.48   276.5 1800.79   282.5  1802.1   285.9 1803.18   294.1 1803.58
     308 1802.74   312.4 1802.85   324.6 1803.81   336.6 1805.21   351.5 1805.63
#Mann= 6 ,-1,0
       0     .07       0      70     .05       0  146.07     .06       0
   196.6    .045       0   221.9     .06       0  282.47     .07       0
Bank Sta=196.6,221.9
XS Rating Curve= 0 ,0
Exp/Cntr=0.3,0.1

Type RM Length L Ch R = 1 ,251     ,46.4,45.1,43.7
XS GIS Cut Line= 4
2191458.46287153663609.281106845 2191605.5078137663575.972584031
2191651.00238145663558.9121211272191751.23545573663506.393434967
#Sta/Elev= 30
       0 1796.76    18.2 1796.91    26.4 1796.22      51 1795.02    63.3 1794.16
   104.3 1794.14   112.5 1793.89   124.8 1792.95   141.2 1790.71   151.9 1790.24
   167.4 1788.09   170.5 1787.42     175 1786.82   183.5 1786.46   187.8  1786.8
   190.51787.999   192.1 1788.77   195.4 1791.03   201.5 1795.63   204.5 1797.43
   209.7 1798.99   211.7 1799.23   214.2 1799.47   231.1 1799.78     246 1800.69
   263.7 1800.47   289.3 1800.93   297.9 1801.36   309.1 1802.35   312.5 1802.42
#Mann= 7 ,-1,0
       0     .07       0      20     .05       0     120     .06       0
   167.4    .045       0   190.5     .06       0  229.36      .1       0
  239.36     .07       0
Bank Sta=167.4,190.5
XS Rating Curve= 0 ,0
Exp/Cntr(USF)=0,0
Exp/Cntr=0.3,0.1

Type RM Length L Ch R = 1 ,206     ,47.8,42.9,40
XS GIS Cut Line= 4
2191506.74505641  663676.17843452191607.35236342663626.259231049
 2191688.3743849 663588.671695312191767.72885569663539.380234877
#Sta/Elev= 30
       0 1796.02    18.2 1796.45    32.9 1796.39    41.8 1795.75    50.7 1794.72
      57 1794.44    83.9 1794.08    96.7 1794.56   114.9 1793.91   119.8 1793.29
   124.4 1792.18   134.8 1788.02   140.9 1786.34   144.1 1785.67   148.5 1785.38
   161.7 1785.86   164.9  1786.3   166.1 1786.55     168  1787.4     171 1789.08
     177 1793.04     180 1794.67     189 1797.68   195.1 1798.61   215.5 1799.12
   224.4 1799.64     231 1800.39   267.3 1800.11   282.4 1800.43     295 1801.12
#Mann= 5 ,-1,0
       0     .06       0   140.9    .045       0   164.9     .06       0
  182.31      .1       0  291.63     .07       0
Bank Sta=140.9,164.9
XS Rating Curve= 0 ,0
Exp/Cntr(USF)=0,0
Exp/Cntr=0.3,0.1

Type RM Length L Ch R = 1 ,163     ,44.6,44.2,43.7
XS GIS Cut Line= 4
2191559.13585626663747.9732343022191611.19463467 663692.14621238
2191698.93415818663618.2175397952191789.07325563663551.022634845
#Sta/Elev= 30
       0 1798.21      14 1798.23      31 1797.69    36.7 1797.46    48.4 1796.47
      66  1795.7    79.1 1795.78    82.8 1795.52    93.3 1795.57    98.5 1794.59
     116 1788.78   129.9 1786.39   133.1 1785.25   135.2 1784.51   136.8 1784.26
   147.3 1783.85   150.1 1783.96   152.9 1784.79   158.6 1787.07   166.5  1789.8
     177 1794.84   180.3 1796.23   186.5  1798.1   192.7 1799.41   198.4 1799.75
   219.6 1799.99   232.5 1800.54   282.4  1800.1   293.2 1800.34   303.5 1800.86
#Mann= 4 ,-1,0
       0     .05       0      20      .1       0   133.1    .045       0
   152.9      .1       0
Bank Sta=133.1,152.9
XS Rating Curve= 0 ,0
Exp/Cntr(USF)=0,0
Exp/Cntr=0.3,0.1

Type RM Length L Ch R = 1 ,119     ,85.5,86,85.5
XS GIS Cut Line= 4
 2191583.3908562663782.9004342062191658.31400841663712.456287266
2191727.36826302663648.2764506262191824.00045553663581.098834762
#Sta/Elev= 30
       0 1792.66     8.4 1792.35    25.9 1792.31      67 1791.54      98  1791.7
   116.3 1789.44   119.4 1788.64   125.3 1786.49   131.2 1784.98   134.8 1783.77
   138.1    1783   142.9 1782.79   149.1 1783.02     1511783.682     160 1787.76
   172.3 1789.06   178.2 1790.41   187.3 1792.98     203 1795.88   212.7 1798.38
   217.6 1799.07   227.3 1799.33   234.4 1799.24   245.9 1799.83   263.1 1800.03
   271.2 1798.89   280.9 1796.87   285.8 1797.19   293.6 1798.42   314.8 1799.57
#Mann= 3 ,-1,0
       0      .1       0   134.8    .045       0     151      .1       0
Bank Sta=134.8,151
XS Rating Curve= 0 ,0
Exp/Cntr(USF)=0,0
Exp/Cntr=0.3,0.1

Type RM Length L Ch R = 1 ,33      ,33,33,33
XS GIS Cut Line= 5
2191532.94045633663808.1256341372191655.46128597663800.309619439
2191767.52114131663738.0266280182191843.79613677663685.401834075
2191894.23557151663555.965287804
#Sta/Elev= 30
       0 1796.94     3.2 1796.29    11.3 1793.91    15.3 1793.05    23.3 1792.44
    35.3 1792.36    39.3  1792.1    47.3 1791.23    60.2 1789.32    79.4  1784.8
    87.4 1782.54    90.2 1782.13   103.1 1781.43   137.4 1781.34   198.8 1781.59
   220.4 1781.66   308.8 1781.76   322.9 1782.67     337 1786.27   348.2 1788.29
   352.5 1788.42   395.4 1787.39   408.3 1787.49   415.2 1787.85   454.9 1790.54
   464.1 1791.54   468.4 1792.69   473.9 1795.01   476.9 1796.63   482.6 1798.24
#Mann= 4 ,-1,0
       0     .05       0      40      .1       0   198.8    .045       0
   220.4      .1       0
#XS Ineff= 2 , 0
          177.46 1788.77  225.63         1788.54
Permanent Ineff=
       T       T
Bank Sta=198.8,220.4
XS Rating Curve= 0 ,0
Exp/Cntr=0.3,0.1
LCMann Table=0

Chan Stop Cuts=-1
Use User Specified Reach Order=0
Composite Channel Slope=5